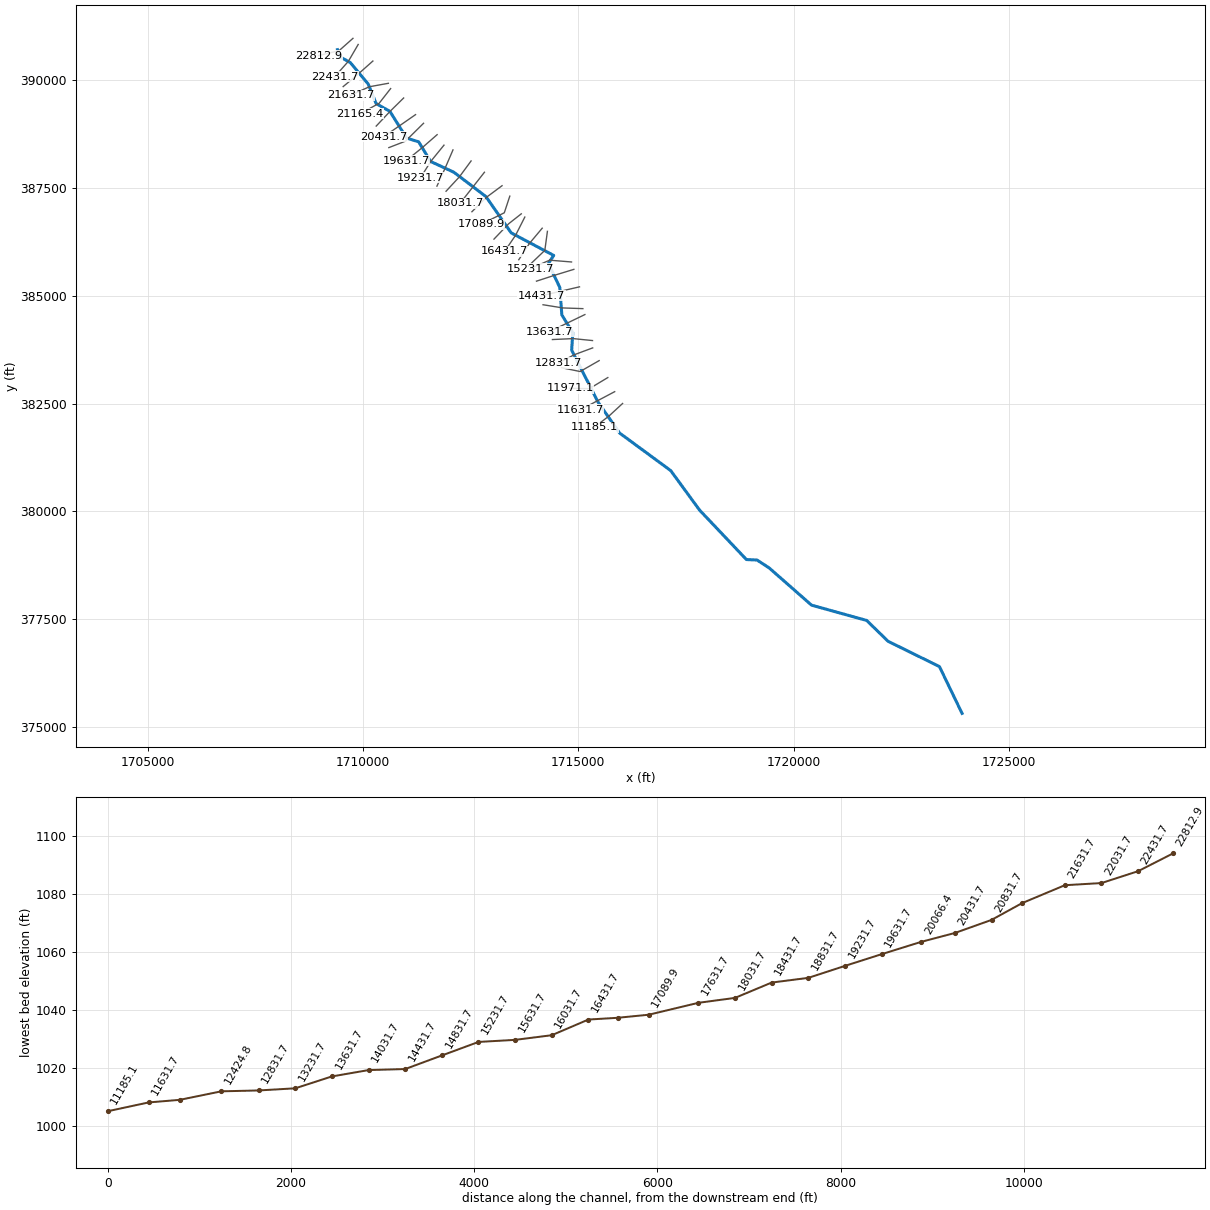
--- DntsRn.prj (project) ---

Proj Title=DntsRn
Current Plan=p01
Default Exp/Contr=0,0
English Units
Geom File=g01
Flow File=f01
Plan File=p01
BEGIN DESCRIPTION:
END DESCRIPTION:
DSS Export Rating Curves= 0
DSS Export Rating Curve Sorted= 0
DSS Export Volume Flow Curves= 0
DXF OffsetX= 0
DXF OffsetY= 0
DXF ScaleX= 0
DXF ScaleY= 0

--- DntsRn.p01 (plan) ---

Plan Title=Floodplain
Program Version=4.00
Geom File=g01
Flow File=f01
K Sum by GR=0
Std Step Tol=0.01
Critical Tol=0.01
Num of Std Step Trials=20
Max Error Tol=0.3
Flow Tol Ratio=0.001
Split Flow NTrial=30
Split Flow Tol=0.02
Split Flow Ratio=0.02
Log Output Level=0
Friction Slope Method=1
Unsteady Friction Slope Method=2
Unsteady Bridges Friction Slope Method=1
Global Log Level=0
CheckData=False
Run HTab=0
Run UNet=0
Run PostProcess=0
UNET Theta=0
UNET Theta Warmup=0
UNET ZTol=0
UNET ZSATol=0
UNET MxIter=0
UNET MaxInSteps=0
UNET DtIC=0
UNET DtMin=0
UNET MaxCRTS=0
UNET WFStab=0
UNET SFStab=0
UNET WFX=0
UNET SFX=0
UNET DSS MLevel=0
UNET DZMax Abort=0
UNET Convert EG Bridges=0
UNET Use Existing IB Tables=0
UNET Froude Limit=0
UNET Froude Power=0
Write IC File=0
Echo Input=False
Echo Output=False
Write Detailed=0

--- DntsRn.f01 (steady flow) ---

Flow Title=NFF Regression Equation
Program Version=4.00
Number of Profiles=1
Profile Names=P100yr
River Rch & RM=DntsRn,Main      ,22812.9
584.1514
River Rch & RM=DntsRn,Main      ,22031.7
627.6647
River Rch & RM=DntsRn,Main      ,21631.7
650.9672
River Rch & RM=DntsRn,Main      ,20431.7
717.7026
River Rch & RM=DntsRn,Main      ,19631.7
776.3647
River Rch & RM=DntsRn,Main      ,17089.9
820.4076
River Rch & RM=DntsRn,Main      ,17089.9
965.1096
River Rch & RM=DntsRn,Main      ,15631.7
1027.066
River Rch & RM=DntsRn,Main      ,15231.7
1375.576
River Rch & RM=DntsRn,Main      ,13631.7
1430.050
River Rch & RM=DntsRn,Main      ,11971.1
1545.186
River Rch & RM=DntsRn,Main      ,6216.3
1672.216
River Rch & RM=DntsRn,Main      ,6031.7
2000.376
River Rch & RM=DntsRn,Main      ,3231.7
2111.543
River Rch & RM=DntsRn,Main      ,31.7
2343.870
River Rch & RM=DntsRn,Main      ,31.7
2345.787
Boundary for River Rch & Prof#=DntsRn,Main      ,1
Up Type=0
Dn Type=3
Dn Slope=0.003406

--- DntsRn.g01 (geometry) ---

Geom Title=USGS 3m DEM
Program Version=4.00

River Reach=DntsRn          ,Main
Reach XY= 30
     1709407.119      390715.256     1709449.037      390558.078
     1709703.694      390416.738     1710119.977      389917.997
     1710304.249      389463.822     1710623.838      389283.299
     1711011.854      388664.322     1711293.718      388574.504
     1711567.358      388121.019     1712109.821      387869.926
     1712854.121      387305.445     1713442.304      386461.302
      1714429.06      385938.516     1714306.216      385750.819
     1714571.941      385192.541     1714617.766       384557.82
     1714871.601      384146.155     1714846.489      383739.116
     1715462.346      382526.903     1715959.715      381814.769
      1717147.19      380942.584      1717817.91      380024.697
     1718905.239      378877.827     1719152.688      378866.048
      1719433.07      378683.643     1720417.805      377819.409
     1721699.589      377463.292     1722194.781      376980.535
      1723388.85      376392.708     1723914.173      375306.387

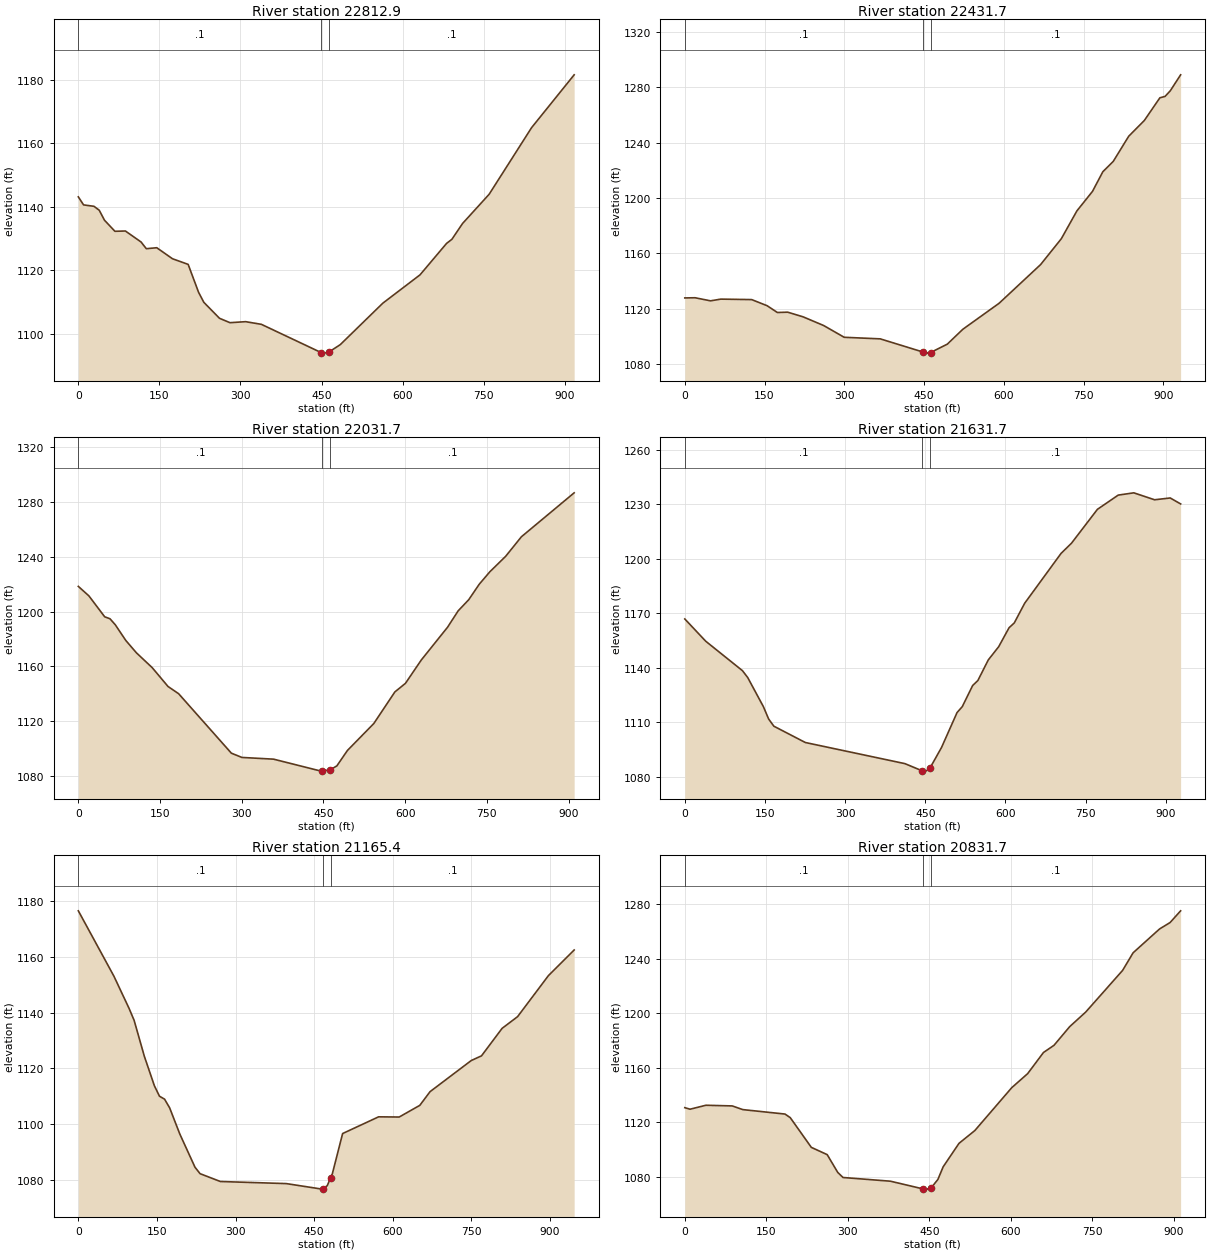
Type RM Length L Ch R = 1 ,22812.9 ,363.11,381.194,394.075
XS GIS Cut Line= 3
     1709766.545      390978.529     1709448.042      390696.031
     1708970.766      390578.008
#Sta/Elev= 30
       0 1143.11     9.7 1140.59      29 1140.14    38.7  1138.9    48.4 1135.77
    67.7 1132.28    87.1 1132.37   116.1 1128.91   125.8  1126.8   145.1 1127.11
   174.2 1123.64   203.2 1121.87   222.5 1113.08   232.2 1109.93   261.2  1104.9
   280.6 1103.52   309.6 1103.84   338.7    1103   449.1 1094.13   455.2 1093.94
   464.1 1094.33   484.7 1096.62   563.4 1109.66   632.2 1118.57   681.4 1128.48
   691.2 1129.76   710.9 1134.73   760.1 1143.93   838.7 1164.91   917.4 1181.52
#Mann= 3 , 0 , 0
       0      .1       0   449.1    .045       0   464.1      .1       0
Bank Sta=449.1,464.1
XS Rating Curve= 0 ,0
Exp/Cntr=0.3,0.1

Type RM Length L Ch R = 1 ,22431.7 ,414.997,400,396.669
XS GIS Cut Line= 3
     1709887.928      390836.367     1709658.838      390443.541
     1709341.141      390086.493
#Sta/Elev= 30
       0 1127.74    19.4 1127.86    48.4 1125.63    67.7 1126.87   125.8 1126.53
   154.8 1122.11   174.2 1117.19   193.5 1117.43   222.5 1114.06   261.2 1107.78
   299.9 1099.26   367.7 1098.12   447.2  1088.7   454.7  1087.8   462.2 1088.21
   493.8 1094.29     523 1105.05   591.3 1123.89   669.3 1151.86   708.3 1170.57
   737.6 1190.72   766.9 1204.81   786.4 1219.05   805.9 1226.48   835.1 1244.74
   864.4  1256.1   893.7 1272.54   903.4 1273.53   913.2 1277.58   932.7 1289.15
#Mann= 3 , 0 , 0
       0      .1       0   447.2    .045       0   462.2      .1       0
Bank Sta=447.2,462.2
XS Rating Curve= 0 ,0
Exp/Cntr=0.3,0.1

Type RM Length L Ch R = 1 ,22031.7 ,412.563,400,393.965
XS GIS Cut Line= 3
     1710229.084      390451.774     1709888.734      390149.368
     1709539.061      389858.323
#Sta/Elev= 30
       0  1218.3    19.4 1211.39    48.4 1196.15    58.1 1194.72    67.8 1190.37
    87.2 1178.88   106.6 1169.92   135.6  1159.1   164.7 1145.36   184.1 1140.12
   280.9  1096.8   300.3 1093.68   358.4 1092.43   445.6 1083.71   447.8 1083.75
   462.8 1084.74   474.6 1087.53     494 1098.77   542.4 1118.39   581.1 1141.42
   600.5 1147.67   629.5 1164.63   677.9  1188.6   697.3  1200.5   716.6 1208.56
     736 1219.89   755.4 1228.93   784.4 1240.19   813.4 1254.47   910.2 1286.47
#Mann= 3 , 0 , 0
       0      .1       0   447.8    .045       0   462.8      .1       0
Bank Sta=447.8,462.8
XS Rating Curve= 0 ,0
Exp/Cntr=0.3,0.1

Type RM Length L Ch R = 1 ,21631.7 ,460.651,466.364,464.682
XS GIS Cut Line= 3
     1710588.784      389934.675     1710144.889      389853.974
     1709712.022      389654.307
#Sta/Elev= 30
       0 1166.76    39.2  1154.5   107.9 1138.28   117.7 1134.53   147.1 1118.46
   156.9 1111.66   166.7  1107.7   225.6 1098.72   411.9 1087.09   443.7 1083.19
   451.2 1082.96   458.7 1084.59   480.4 1095.95   509.5 1115.21   519.3 1118.48
   538.7  1130.1   548.5 1132.87   567.9 1144.18   587.4 1151.47   606.8 1161.92
   616.6 1164.58     636 1175.39   704.1 1202.85   723.6 1208.46   772.2 1227.14
   811.1 1234.97   840.3 1236.23   879.2  1232.4   908.4  1233.4   927.9 1230.12
#Mann= 3 , 0 , 0
       0      .1       0   443.7    .045       0   458.7      .1       0
Bank Sta=443.7,458.7
XS Rating Curve= 0 ,0
Exp/Cntr=0.3,0.1

Type RM Length L Ch R = 1 ,21165.4 ,325.593,333.636,344.193
XS GIS Cut Line= 3
     1710641.438      389812.322     1710373.085      389469.102
     1709924.411      389225.378
#Sta/Elev= 30
       0 1176.48    67.8 1153.11    96.8 1141.54   106.5 1137.24   125.9 1124.42
   145.2 1113.79   154.9 1110.06   164.6 1109.01   174.3 1105.89   193.6 1096.56
   222.7 1084.61   232.4 1082.31   271.1 1079.51   396.9 1078.76   465.1 1076.78
   466.5 1076.95     475 1077.99   481.5 1080.84   484.8 1082.28   504.4 1096.69
   573.1 1102.68   612.4 1102.61   651.7 1106.79   671.3  1111.7   749.9 1122.85
   769.5 1124.53   808.8 1134.38   838.3 1138.56   897.2 1153.27   946.3 1162.45
#Mann= 3 , 0 , 0
       0      .1       0   466.5    .045       0   481.5      .1       0
Bank Sta=466.5,481.5
XS Rating Curve= 0 ,0
Exp/Cntr=0.3,0.1

Type RM Length L Ch R = 1 ,20831.7 ,403.902,400,395.082
XS GIS Cut Line= 3
     1710943.621      389593.734     1710625.485      389280.743
     1710306.227      388941.246
#Sta/Elev= 30
       0 1130.73     9.7  1129.6    38.8  1132.5    87.3 1132.01   106.7 1129.31
   184.3 1126.05     194 1123.43   232.8 1101.62     262 1096.29   281.4 1083.26
   291.1 1079.52   378.4  1076.8   438.8 1071.11   446.3 1070.99   453.8 1072.16
   465.7  1078.1   475.4 1087.37   504.5 1104.55   533.7 1113.97   601.6  1145.4
   630.8 1155.67   659.9 1171.17   679.3 1176.46   708.4 1190.23   737.6 1200.82
   805.5 1231.37   824.9 1244.32   873.5 1261.78   892.9  1266.5   912.3 1275.09
#Mann= 3 , 0 , 0
       0      .1       0   438.8    .045       0   453.8      .1       0
Bank Sta=438.8,453.8
XS Rating Curve= 0 ,0
Exp/Cntr=0.3,0.1

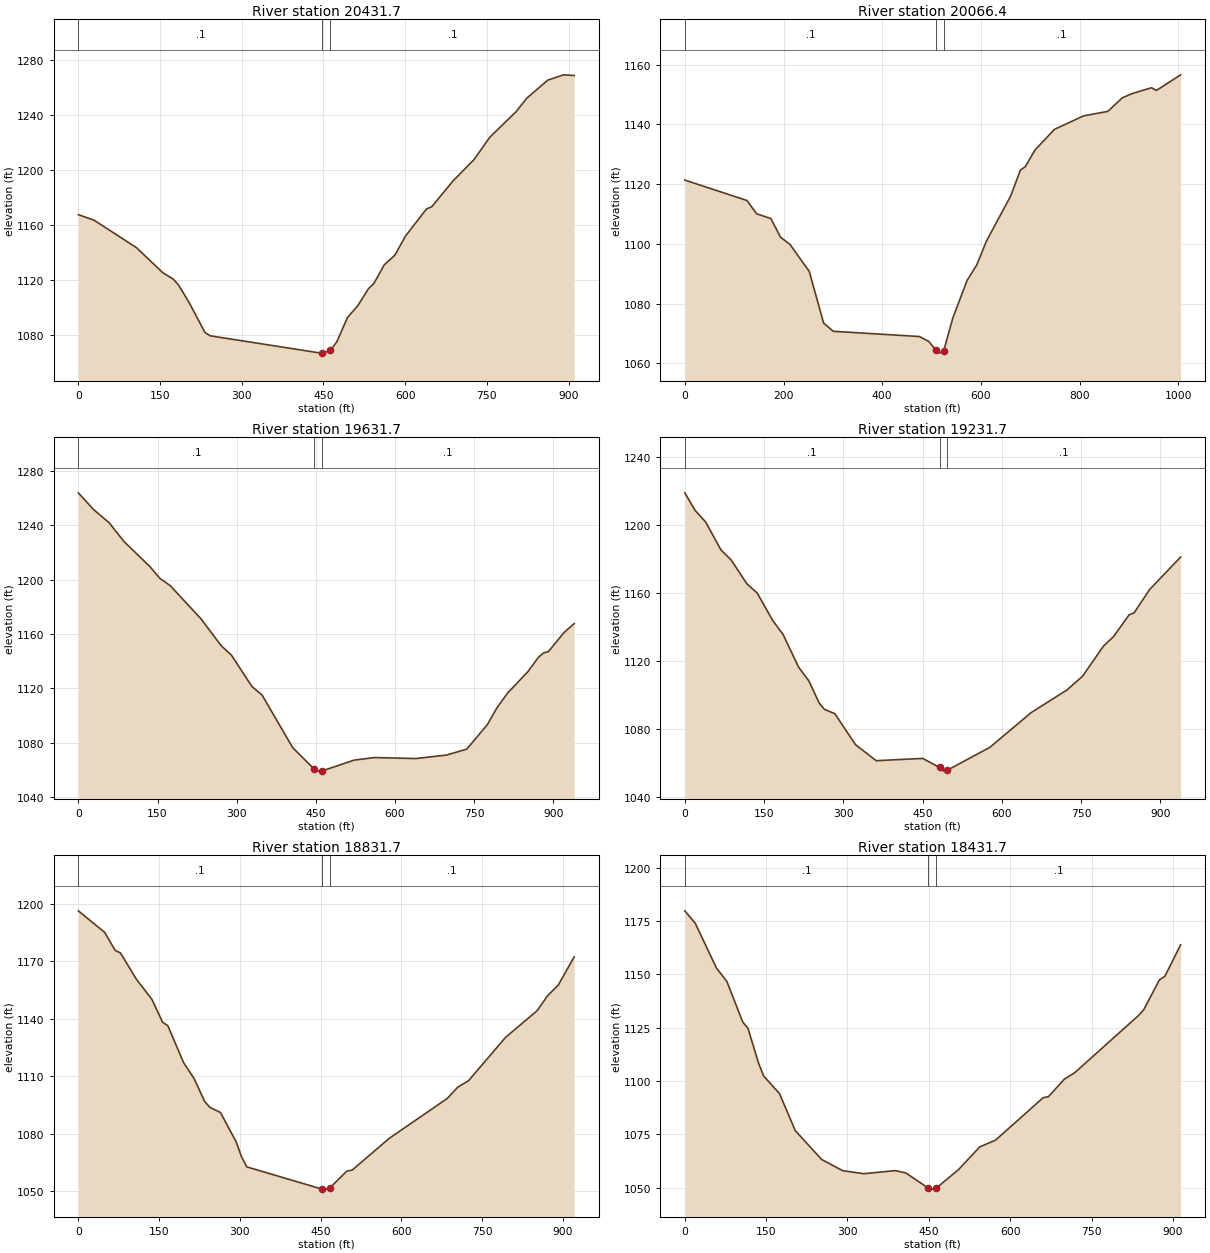
Type RM Length L Ch R = 1 ,20431.7 ,361.468,365.345,369.317
XS GIS Cut Line= 3
     1711220.239      389207.262     1710846.319       388947.72
     1710471.467      388689.876
#Sta/Elev= 30
       0 1167.27    29.1 1163.17   106.5 1143.31     155 1125.03   174.3 1120.34
     184 1116.01   203.4 1103.29   232.4 1081.52   242.1 1079.08   445.5 1066.48
   447.7 1066.52   462.7  1068.4   474.5 1074.75   493.9 1092.31   513.2 1101.14
   532.6 1113.44   542.3 1117.04   561.6 1130.78     581 1137.75   600.4 1151.63
   639.1 1171.45   648.8 1173.03   687.5 1191.72   726.2 1207.29   755.3 1223.63
   803.7 1242.26     823 1251.98   861.7 1265.17   890.8 1269.03   910.1 1268.52
#Mann= 3 , 0 , 0
       0      .1       0   447.7    .045       0   462.7      .1       0
Bank Sta=447.7,462.7
XS Rating Curve= 0 ,0
Exp/Cntr=0.3,0.1

Type RM Length L Ch R = 1 ,20066.4 ,434.961,434.655,429.956
XS GIS Cut Line= 3
     1711406.143       389006.58     1710985.165      388591.142
     1710600.192      388441.584
#Sta/Elev= 30
       0 1121.36     126 1114.52   145.4 1110.09   174.5 1108.46   193.9 1102.25
   213.3 1099.78   252.1  1090.8   281.2 1073.52   300.6 1070.75   475.1    1069
   494.5 1067.33   509.2 1064.32   513.9 1063.44   524.2 1064.01     543  1075.2
   572.1 1087.84   591.4 1092.92   611.1 1100.93   660.3 1116.06   679.9 1124.68
   689.8 1125.84   709.4 1131.41   748.8 1138.32   807.8 1142.84     857 1144.34
   886.5  1148.9   906.1 1150.29   945.5 1152.26   955.3 1151.34  1004.5 1156.58
#Mann= 3 , 0 , 0
       0      .1       0   509.2    .045       0   524.2      .1       0
Bank Sta=509.2,524.2
XS Rating Curve= 0 ,0
Exp/Cntr=0.3,0.1

Type RM Length L Ch R = 1 ,19631.7 ,396.374,400,410.753
XS GIS Cut Line= 3
      1711721.28      388741.943     1711378.777      388443.075
     1711001.941      388138.023
#Sta/Elev= 30
       0 1263.74      29 1251.41      58 1241.89      87 1227.76   135.4  1209.6
   154.7 1200.79   174.1 1195.52   232.1 1171.25   270.8 1151.32   290.1 1144.39
   328.8 1121.42   348.2 1115.05   406.2 1076.39   447.1 1060.62   454.6 1059.16
   462.1 1059.36   522.4 1067.23   561.2 1069.14   638.8 1068.41     697 1070.94
   735.8  1075.3   774.6 1093.17   793.9 1106.15   813.3 1116.54   852.1 1132.45
   871.5 1142.74   881.2    1146   890.9 1147.12     920 1160.99   939.4 1167.62
#Mann= 3 , 0 , 0
       0      .1       0   447.1    .045       0   462.1      .1       0
Bank Sta=447.1,462.1
XS Rating Curve= 0 ,0
Exp/Cntr=0.3,0.1

Type RM Length L Ch R = 1 ,19231.7 ,389.803,400,399.364
XS GIS Cut Line= 3
     1711880.265      388498.676       1711571.4       388118.78
     1711333.551      387738.139
#Sta/Elev= 30
       0  1218.9    19.6 1208.53    39.2 1201.85    68.5 1185.29    88.1 1179.25
   117.5 1165.36   137.1 1159.92   166.5 1143.74   186.1 1135.51   215.4  1116.3
     235 1108.14   254.6 1095.05   264.4 1091.47     284 1088.93   323.1  1070.7
   362.3 1061.26   450.4 1062.61   482.1  1057.3   489.6 1055.12   497.1 1055.69
   577.4 1069.11   655.5 1089.54   723.8 1102.98   753.1 1111.06   792.1 1128.55
   811.6 1134.34   840.9 1147.07   850.6 1148.31   879.9 1162.03   938.5 1181.11
#Mann= 3 , 0 , 0
       0      .1       0   482.1    .045       0   497.1      .1       0
Bank Sta=482.1,497.1
XS Rating Curve= 0 ,0
Exp/Cntr=0.3,0.1

Type RM Length L Ch R = 1 ,18831.7 ,404.847,400,392.965
XS GIS Cut Line= 3
     1712089.454      388388.411     1711907.982      387966.402
     1711716.755      387546.718
#Sta/Elev= 30
       0  1196.2    48.9 1184.97    68.4 1175.54    78.2 1174.24   107.5 1160.63
   136.8 1149.94   156.4 1138.07   166.2 1136.26   195.5 1116.96     215 1108.66
   234.6 1096.72   244.3 1093.65   263.9 1090.98   293.2 1075.57     303 1067.87
   312.8  1062.6   451.9 1051.05   459.4 1050.99   466.9 1051.64   498.6  1060.4
   508.4 1060.91   577.1 1077.45   685.1 1098.32   704.7 1104.26   724.3  1107.5
     793 1130.11   851.9  1144.1   871.5 1151.99   891.1 1157.45   920.6 1172.14
#Mann= 3 , 0 , 0
       0      .1       0   451.9    .045       0   466.9      .1       0
Bank Sta=451.9,466.9
XS Rating Curve= 0 ,0
Exp/Cntr=0.3,0.1

Type RM Length L Ch R = 1 ,18431.7 ,400.895,400,401.702
XS GIS Cut Line= 3
     1712510.277      388132.057     1712239.979      387764.518
     1711928.583      387428.554
#Sta/Elev= 30
       0 1179.76    19.4  1173.9    58.2 1153.03    77.7 1146.61   106.8 1127.69
   116.5 1124.72   135.9 1108.48   145.6 1102.32   174.7 1094.09   203.8 1076.74
   252.4 1063.26   291.2 1058.01     330  1056.6   388.3 1058.05   407.7 1056.94
   448.7 1049.91   456.2 1049.37   463.7 1049.84     505 1058.59   543.9 1069.16
   573.2 1072.36   660.9 1092.22   670.7 1092.73   699.9 1100.91   719.4 1104.01
   836.3 1130.63   846.1 1133.33   875.3 1147.45   885.1 1149.01   914.3 1163.85
#Mann= 3 , 0 , 0
       0      .1       0   448.7    .045       0   463.7      .1       0
Bank Sta=448.7,463.7
XS Rating Curve= 0 ,0
Exp/Cntr=0.3,0.1

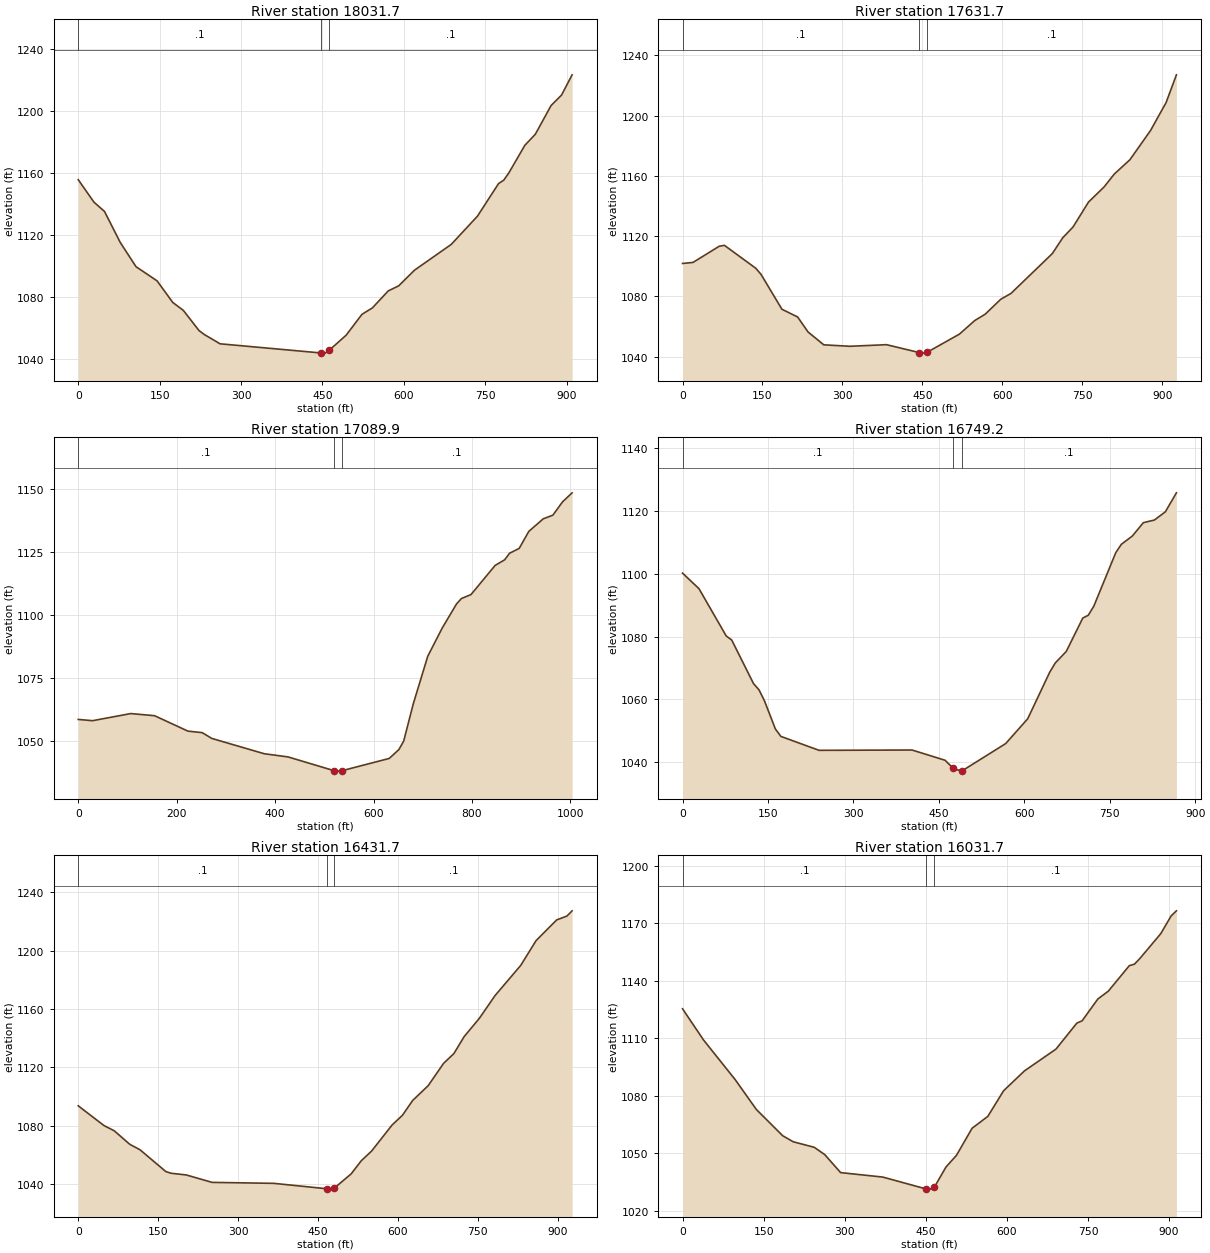
Type RM Length L Ch R = 1 ,18031.7 ,406.144,400,397.132
XS GIS Cut Line= 3
     1712820.351      387869.437     1712539.335       387511.59
     1712258.318      387153.742
#Sta/Elev= 30
       0 1155.83      29 1141.35    48.4 1135.38    77.4 1115.41   106.5 1099.76
   145.2 1090.67   174.3 1076.69   193.6 1071.64   222.7 1058.56   232.3 1056.07
   261.4 1050.08   447.5 1044.18     455 1044.08   462.5 1045.93   493.7 1055.65
   522.8 1069.08   542.1 1073.24   571.2 1084.17   590.5 1087.44   619.6 1097.52
   687.3 1114.13   735.7 1132.36   774.5 1153.33   784.1 1155.52   793.8 1160.41
   822.9 1177.97   842.2 1185.09   871.3 1203.61   890.6 1210.38     910 1223.39
#Mann= 3 , 0 , 0
       0      .1       0   447.5    .045       0   462.5      .1       0
Bank Sta=447.5,462.5
XS Rating Curve= 0 ,0
Exp/Cntr=0.3,0.1

Type RM Length L Ch R = 1 ,17631.7 ,545.621,541.866,534.835
XS GIS Cut Line= 3
     1713229.543      387557.039     1712866.936      387288.163
     1712529.919      386953.015
#Sta/Elev= 30
       0 1101.89    19.6 1102.58    68.7  1113.3    78.5 1113.94   137.4 1098.72
   147.2  1094.7   186.5  1071.5   215.9 1066.39   235.5 1056.43     265 1047.89
     314 1046.92   382.7 1047.99   443.9 1042.77   451.4 1042.38   458.9 1042.95
   519.3 1054.94   548.4 1064.03   567.8  1068.2   596.9 1078.09   616.3 1082.03
   693.9 1108.47   713.3  1118.9   732.7 1126.11   761.8 1142.67   790.9 1152.66
   810.3 1161.32   839.4 1170.73   878.2 1190.19   907.3 1208.67   926.7 1227.11
#Mann= 3 , 0 , 0
       0      .1       0   443.9    .045       0   458.9      .1       0
Bank Sta=443.9,458.9
XS Rating Curve= 0 ,0
Exp/Cntr=0.3,0.1

Type RM Length L Ch R = 1 ,17089.9 ,328.597,340.631,349.532
XS GIS Cut Line= 3
     1713409.462      387314.976     1713281.689      386928.675
     1712746.797      386664.537
#Sta/Elev= 30
       0 1058.71    29.1 1058.21   106.6 1061.02     155 1060.19   222.8 1054.09
   251.9 1053.48   271.3  1051.2   377.8 1045.15   426.4 1043.88   520.1 1038.43
   524.2 1038.27   535.1  1038.4   631.8 1043.28   651.4 1046.77   661.2 1050.13
   680.7 1064.85   710.1 1083.67   739.4  1094.8   768.7  1104.4   778.5  1106.5
   798.1 1108.09     847 1119.59   866.5 1121.83   876.3  1124.4   895.9 1126.32
   915.4 1133.03   944.8 1138.02   964.3 1139.45   983.9 1144.71  1003.4 1148.29
#Mann= 3 , 0 , 0
       0      .1       0   520.1    .045       0   535.1      .1       0
Bank Sta=520.1,535.1
XS Rating Curve= 0 ,0
Exp/Cntr=0.3,0.1

Type RM Length L Ch R = 1 ,16749.2 ,309.785,317.503,321.423
XS GIS Cut Line= 3
     1713676.236      386904.362     1713382.395      386673.037
     1713041.544      386316.694
#Sta/Elev= 30
       0 1100.14    28.8 1095.22    76.7 1080.17    86.3  1078.9   124.7 1065.01
   134.2 1063.06   143.8 1059.57     163 1050.61   172.6 1048.25   239.7 1043.82
     403 1043.92     461 1040.66   475.3 1038.08     490 1037.21   490.3 1037.24
   567.3 1045.96     606 1053.85   644.7 1068.67   654.4 1071.59   673.7 1075.25
   702.7 1085.86   712.4 1086.77     722 1089.61   760.7 1106.68   770.4  1109.3
   789.7 1111.94   809.1 1116.19   828.4 1117.02   847.7 1119.64   867.1 1125.67
#Mann= 3 , 0 , 0
       0      .1       0   475.3    .045       0   490.3      .1       0
Bank Sta=475.3,490.3
XS Rating Curve= 0 ,0
Exp/Cntr=0.3,0.1

Type RM Length L Ch R = 1 ,16431.7 ,406.05,400,399.927
XS GIS Cut Line= 3
     1713758.153      386829.162     1713543.856      386406.739
     1713288.458      386031.717
#Sta/Elev= 30
       0 1093.67    48.3 1080.17    67.7 1076.55    96.7 1067.33     116 1063.58
   164.3  1048.7     174  1047.5     203 1046.32   251.3 1041.23   367.3 1040.57
   466.2 1036.89   473.7 1036.61   481.2 1037.45   512.3 1046.97   531.6 1056.08
   550.9 1062.68   589.5 1080.59   608.8 1087.17   628.1 1097.38   657.1 1107.44
   686.1 1122.77   705.4 1129.45   724.7 1141.07   753.6 1153.77   782.6 1169.13
   830.9 1189.84   859.8 1206.84   898.4 1220.98   917.7 1223.66   927.4 1227.22
#Mann= 3 , 0 , 0
       0      .1       0   466.2    .045       0   481.2      .1       0
Bank Sta=466.2,481.2
XS Rating Curve= 0 ,0
Exp/Cntr=0.3,0.1

Type RM Length L Ch R = 1 ,16031.7 ,387.084,400,392.408
XS GIS Cut Line= 3
     1714162.246      386570.833     1713867.866      386219.825
      1713618.27      385838.891
#Sta/Elev= 30
       0 1125.26      39 1108.94    97.5 1088.28   136.5 1072.76   185.2 1059.07
   204.7 1055.91   243.7 1053.01   263.2 1049.16   292.4 1039.81   370.4 1037.49
   450.6 1031.29   458.1  1031.2   465.6 1032.12   487.2 1042.71   506.6  1048.8
   535.6 1062.97   564.7 1069.15   593.8 1082.51   632.5  1092.9   690.7 1104.24
   729.4 1117.83   739.1 1119.01   768.2  1130.4   787.6 1134.49   826.3 1147.76
     836 1148.59   845.7 1151.46   884.5 1164.44   903.8 1173.76   913.5 1176.38
#Mann= 3 , 0 , 0
       0      .1       0   450.6    .045       0   465.6      .1       0
Bank Sta=450.6,465.6
XS Rating Curve= 0 ,0
Exp/Cntr=0.3,0.1

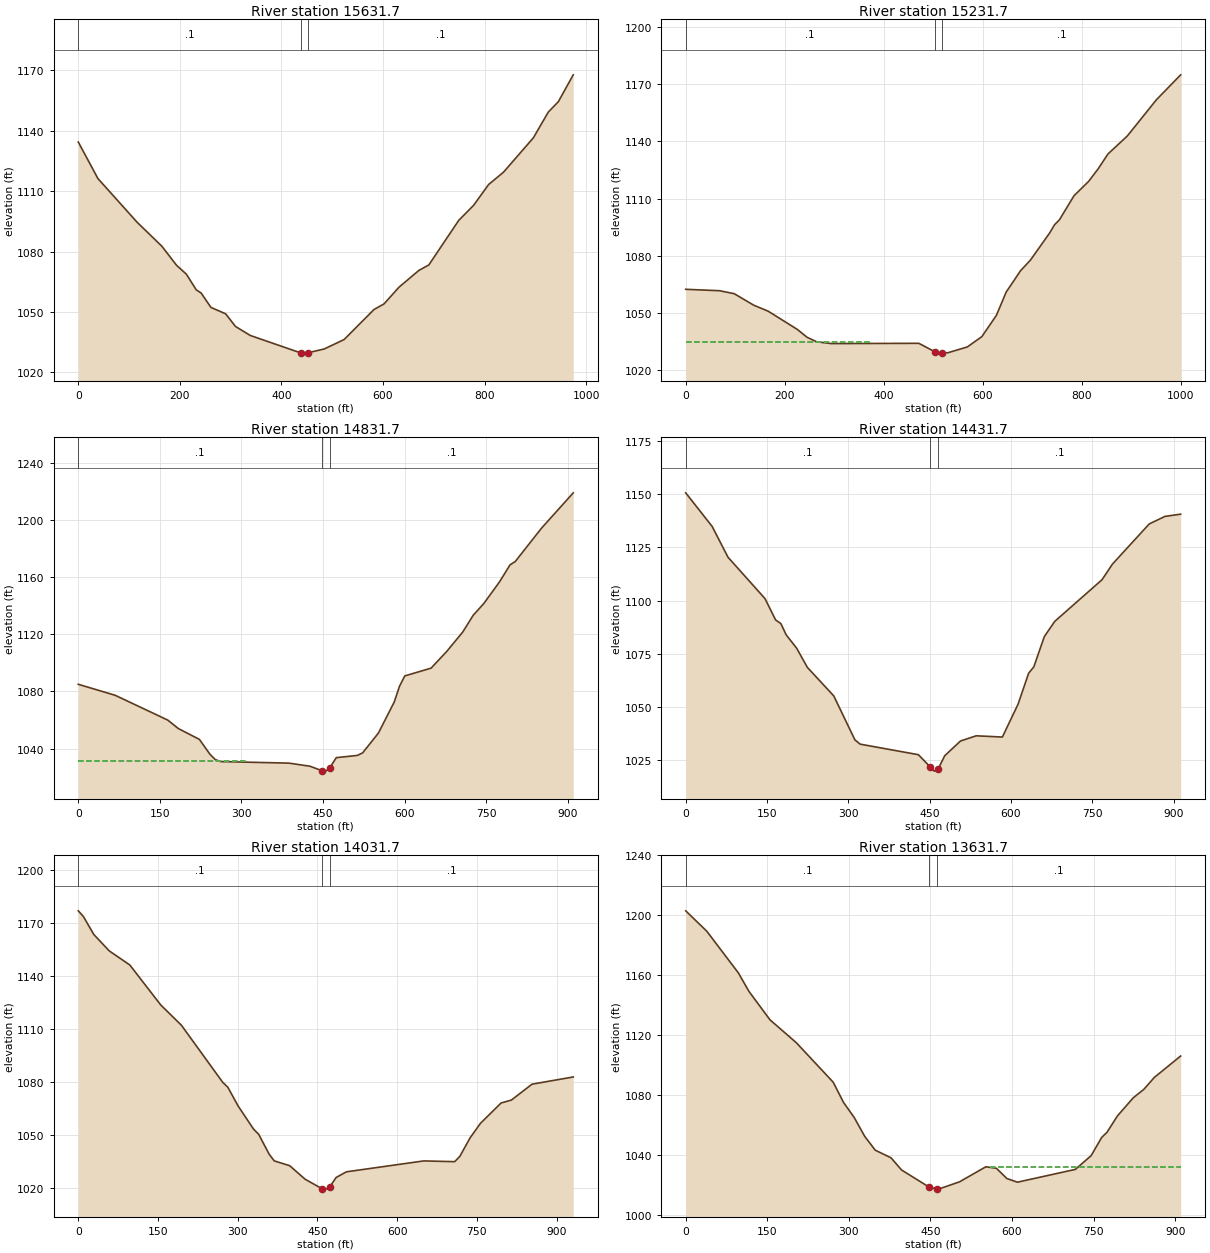
Type RM Length L Ch R = 1 ,15631.7 ,439.4,400,383.253
XS GIS Cut Line= 3
     1714282.925      386497.395      1714223.07      386056.356
     1713840.423      385690.217
#Sta/Elev= 30
       0 1134.42    38.7 1116.27   116.1 1094.52   164.5  1082.7   193.5 1073.22
   212.9 1068.78   232.2 1061.05   241.9 1059.45   261.2  1052.3   290.3  1049.1
   309.6 1042.84   338.6 1038.38   437.6 1029.75   445.1  1029.6   452.6 1029.79
   484.3 1031.66   523.5 1036.35   582.4 1051.27     602 1054.02   631.4  1062.3
   670.7 1070.67   690.3 1073.38   749.1 1095.48   778.5    1103     808 1113.31
   837.4 1119.46   896.2 1136.52   925.6 1149.31   945.3 1154.43   974.7 1167.78
#Mann= 3 , 0 , 0
       0      .1       0   437.6    .045       0   452.6      .1       0
Bank Sta=437.6,452.6
XS Rating Curve= 0 ,0
Exp/Cntr=0.3,0.1

Type RM Length L Ch R = 1 ,15231.7 ,390.571,400,394.956
XS GIS Cut Line= 3
     1714842.941      385786.305     1714334.371      385828.131
     1713885.807      385631.755
#Sta/Elev= 30
       0 1062.37    68.7 1061.62    98.1 1060.06   137.4 1054.04   166.8 1050.86
   225.7 1041.29   245.3 1037.18     265  1034.8   294.4 1033.89     471 1034.03
   502.8 1029.68   510.3 1028.88   517.8 1028.93   529.9 1029.09     569 1032.12
   598.4 1037.56   627.8 1048.73   647.4 1060.87   676.8 1072.21   696.4 1077.65
   735.5    1092   745.3 1096.27   755.1 1098.84   784.5 1111.45   813.9 1118.95
   833.5 1125.64   853.1 1133.37   892.2  1142.8     951 1161.82    1000  1174.9
#Mann= 3 , 0 , 0
       0      .1       0   502.8    .045       0   517.8      .1       0
#XS Ineff= 2 , 0
          372.75 1034.46
Permanent Ineff=
       F       F
Bank Sta=502.8,517.8
XS Rating Curve= 0 ,0
Exp/Cntr=0.3,0.1

Type RM Length L Ch R = 1 ,14831.7 ,401.707,400,398.097
XS GIS Cut Line= 3
     1714897.091      385615.048     1714461.869      385481.682
     1714028.993      385341.016
#Sta/Elev= 30
       0 1084.94    67.8 1077.25   164.6  1059.9     184 1053.99   222.8  1046.4
   242.1 1036.05   251.8 1032.35   261.5 1030.89   387.4 1029.81   426.1 1027.64
   447.7 1024.59   455.2 1024.21   462.7 1026.68   474.6 1033.64   513.3 1035.19
     523 1036.99     552 1050.81   581.1 1072.52   590.8 1083.54   600.5 1090.79
   648.9 1096.23   677.9 1108.01     707 1121.41   726.4 1133.22   745.7 1141.34
   774.8 1156.58   794.1 1168.43   803.8 1170.83   852.2 1194.19   910.4 1218.83
#Mann= 3 , 0 , 0
       0      .1       0   447.7    .045       0   462.7      .1       0
#XS Ineff= 2 , 0
          310.97 1031.14
Permanent Ineff=
       F       F
Bank Sta=447.7,462.7
XS Rating Curve= 0 ,0
Exp/Cntr=0.3,0.1

Type RM Length L Ch R = 1 ,14431.7 ,405.66,400,391.013
XS GIS Cut Line= 3
      1715028.54      385209.337     1714582.038      385105.785
     1714140.229       384999.52
#Sta/Elev= 30
       0 1150.78    48.8 1134.93      78 1120.42   146.3 1100.89   165.8 1090.83
   175.5 1089.12   185.3 1083.82   204.8 1077.43   224.3 1068.48   273.1    1055
   312.1 1034.26   321.8 1032.25   429.1 1027.28   450.9 1021.54   458.4 1019.53
   465.9 1020.71   477.7 1026.79   506.7 1033.73   535.7 1036.19     584  1035.6
     613 1051.13   632.4 1065.69     642  1068.7   661.4    1083   680.7 1090.18
   767.7 1109.78   787.1 1117.19   854.8  1136.1   883.8 1139.66   912.8 1140.72
#Mann= 3 , 0 , 0
       0      .1       0   450.9    .045       0   465.9      .1       0
Bank Sta=450.9,465.9
XS Rating Curve= 0 ,0
Exp/Cntr=0.3,0.1

Type RM Length L Ch R = 1 ,14031.7 ,389.405,400,413.738
XS GIS Cut Line= 3
     1715106.548       384703.17     1714641.225      384719.254
     1714181.621      384793.461
#Sta/Elev= 30
       0 1176.74     9.7  1173.5    29.1 1163.38    58.2 1154.07      97 1146.06
   155.2 1123.42     194 1111.97   271.6 1079.69   281.3 1076.88   300.7 1066.24
   329.8 1053.11   339.5 1050.17   358.9 1039.04   368.6 1035.16   397.7 1032.44
   426.8 1024.77   458.1 1019.48   465.6 1019.17   473.1 1020.49     485 1025.74
   504.4 1028.97   649.9 1035.14   708.1 1034.72   717.8 1037.72   737.2 1048.25
   756.6 1056.43   795.4 1067.94   814.8 1069.59   853.6 1078.59   931.2 1082.68
#Mann= 3 , 0 , 0
       0      .1       0   458.1    .045       0   473.1      .1       0
Bank Sta=458.1,473.1
XS Rating Curve= 0 ,0
Exp/Cntr=0.3,0.1

Type RM Length L Ch R = 1 ,13631.7 ,412.326,400,390.982
XS GIS Cut Line= 3
     1715153.212      384565.204     1714743.304      384367.718
     1714333.396      384170.232
#Sta/Elev= 30
       0 1203.01    38.7 1189.42    96.8 1161.55   116.2 1149.21   154.9 1130.18
   203.3 1114.89   271.1 1088.49   290.4 1074.81   309.8 1064.87   329.1 1052.29
   348.5 1043.01   377.6 1037.89   396.9 1029.76   447.5 1018.36   462.5    1017
   464.7 1016.98   503.4 1021.85   551.8 1031.91   571.2 1030.93   590.5 1024.07
   609.9 1021.62   716.4 1030.17   745.4 1039.36   764.8 1051.53   774.5 1054.95
   793.8 1065.93   822.9 1078.05   842.2 1083.65   861.6 1091.65     910 1105.97
#Mann= 3 , 0 , 0
       0      .1       0   447.5    .045       0   462.5      .1       0
#XS Ineff= 2 , 0
                          561.56         1031.58
Permanent Ineff=
       F       F
Bank Sta=447.5,462.5
XS Rating Curve= 0 ,0
Exp/Cntr=0.3,0.1

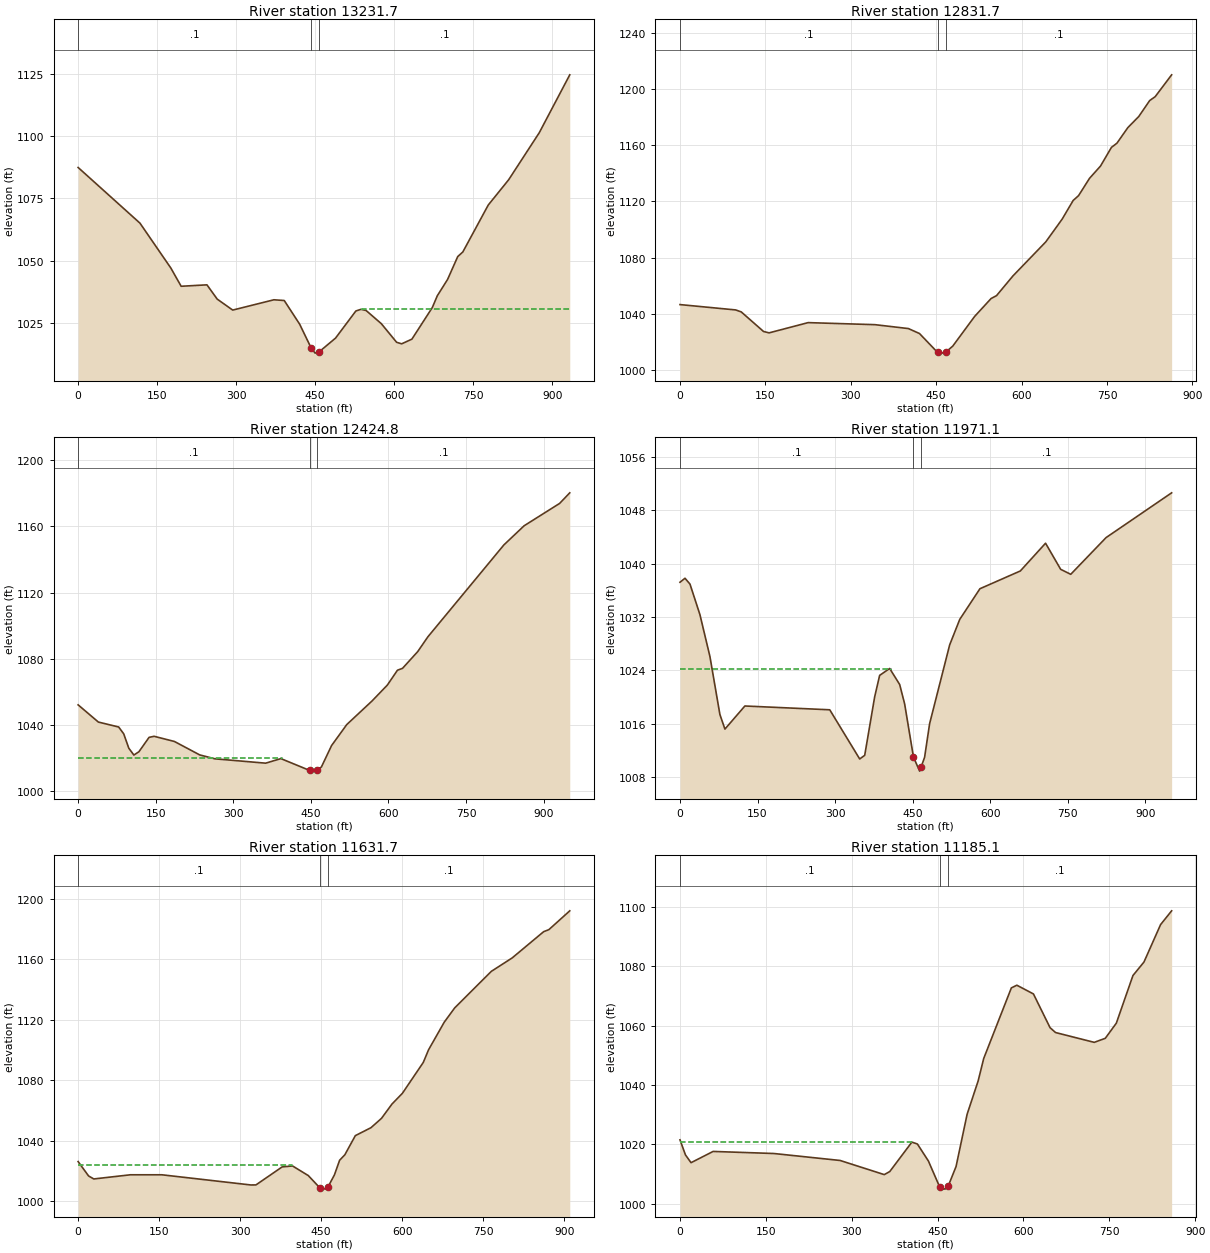
Type RM Length L Ch R = 1 ,13231.7 ,389.582,400,410.085
XS GIS Cut Line= 3
      1715330.23      383962.005      1714882.53      384007.277
     1714399.596      383985.436
#Sta/Elev= 30
       0 1087.46   117.4  1065.1   176.1 1047.04   195.6 1039.74   244.6 1040.31
   264.1 1034.57   293.5 1030.17   371.7 1034.31   391.3 1034.02   420.6 1024.51
   442.5 1014.91     450 1012.88   457.5 1013.39   488.7 1018.91   527.3 1029.81
     537 1030.48   546.7 1030.01   575.7  1024.7   604.7 1017.23   614.3 1016.62
   633.7  1018.5   672.4 1031.18     682 1035.95   701.4 1042.47   720.7 1051.67
   730.4 1053.53   778.7 1072.39   817.4 1082.53   875.4 1101.39   933.4 1124.68
#Mann= 3 , 0 , 0
       0      .1       0   442.5    .045       0   457.5      .1       0
#XS Ineff= 2 , 0
                          539.42         1030.58
Permanent Ineff=
       F       F
Bank Sta=442.5,457.5
XS Rating Curve= 0 ,0
Exp/Cntr=0.3,0.1

Type RM Length L Ch R = 1 ,12831.7 ,403.247,406.963,407.703
XS GIS Cut Line= 3
     1715334.496      383791.538     1714903.507      383631.419
     1714546.859      383442.472
#Sta/Elev= 30
       0 1046.64    97.8 1042.84   107.6 1041.43   146.7 1027.53   156.5 1026.54
     225 1033.82   342.4 1032.37   401.1  1029.6   420.6 1026.07   452.3 1012.67
   459.8 1012.14   467.3 1013.05     479 1017.12   517.4  1038.2   546.3 1050.93
   555.9 1053.01   584.7    1067   642.4 1091.22   671.2 1107.42   690.4 1120.61
     700  1124.1   719.2 1136.39   738.5  1145.1   757.7 1158.39   767.3 1161.35
   786.5 1172.43   805.7 1180.34   824.9 1191.68   834.5 1194.42   863.4 1209.95
#Mann= 3 , 0 , 0
       0      .1       0   452.3    .045       0   467.3      .1       0
Bank Sta=452.3,467.3
XS Rating Curve= 0 ,0
Exp/Cntr=0.3,0.1

Type RM Length L Ch R = 1 ,12424.8 ,453.202,453.679,454.157
XS GIS Cut Line= 3
     1715484.963      383496.217     1715042.616      383243.061
      1714610.56      383331.688
#Sta/Elev= 30
       0 1051.97    39.2 1041.55    78.4 1038.56    88.2 1034.41      98 1025.72
   107.8 1021.57   117.6 1023.59   137.2 1032.29     147 1032.93   186.2  1029.8
   235.2 1021.65   264.6 1019.29   362.6 1016.66   392.1 1019.42   447.6 1012.28
   460.7 1011.84   462.6 1012.33   470.5 1014.39   490.1 1027.32   519.5 1040.04
   568.5 1054.37   597.9 1063.93   617.5 1072.95   627.3 1074.09   656.7 1084.22
   676.3 1093.16   823.3 1148.82   862.5 1160.43   931.1 1173.96   950.7 1180.37
#Mann= 3 , 0 , 0
       0      .1       0   447.6    .045       0   462.6      .1       0
#XS Ineff= 2 , 0
          394.15 1019.74
Permanent Ineff=
       F       F
Bank Sta=447.6,462.6
XS Rating Curve= 0 ,0
Exp/Cntr=0.3,0.1

Type RM Length L Ch R = 1 ,11971.1 ,340.606,339.358,338.11
XS GIS Cut Line= 3
     1715686.215      383102.707     1715255.874       382844.24
     1714807.201      382852.549
#Sta/Elev= 30
       0  1037.2     9.7  1037.8    19.3 1036.93    38.6 1032.34    57.9 1026.07
    77.2 1017.38    86.9  1015.2   125.5 1018.66   289.6 1018.09   347.5 1010.72
   357.2 1011.27   376.5 1020.05   386.1 1023.25   405.5 1024.28   424.8 1021.88
   434.4 1018.98   451.5    1011   463.4  1008.9   466.5 1009.57     473 1010.97
   482.7 1016.01   521.5 1027.82     541 1031.64     580 1036.23   658.1 1038.89
   706.9 1043.05   736.1 1039.14   755.6 1038.39   823.9 1043.89   950.7  1050.6
#Mann= 3 , 0 , 0
       0      .1       0   451.5    .045       0   466.5      .1       0
#XS Ineff= 2 , 0
          407.44 1024.24
Permanent Ineff=
       F       F
Bank Sta=451.5,466.5
XS Rating Curve= 0 ,0
Exp/Cntr=0.3,0.1

Type RM Length L Ch R = 1 ,11631.7 ,442.904,446.672,450.44
XS GIS Cut Line= 3
     1715845.715      382775.297     1715443.393      382562.784
     1715041.071      382350.271
#Sta/Elev= 30
       0 1026.23    19.4 1016.71      29 1014.74    96.8  1017.5   154.9  1017.5
   319.5 1010.77   329.1 1010.78   377.6  1022.7   396.9 1023.34     426 1016.99
   447.5 1008.83     455 1008.01   462.5 1009.48   474.4 1017.42     484  1027.1
   493.7 1030.75   513.1  1043.4   542.1 1048.67   561.5 1054.83   580.9 1064.29
   600.2  1071.4   638.9 1091.86   648.6 1100.18   677.7 1118.49     697 1127.92
   764.8  1152.1   803.5 1161.01   861.6 1178.34   871.3 1179.69     910 1192.15
#Mann= 3 , 0 , 0
       0      .1       0   447.5    .045       0   462.5      .1       0
#XS Ineff= 2 , 0
          395.93 1024.21
Permanent Ineff=
       F       F
Bank Sta=447.5,462.5
XS Rating Curve= 0 ,0
Exp/Cntr=0.3,0.1

Type RM Length L Ch R = 1 ,11185.1 ,363.056,363.77,364.485
XS GIS Cut Line= 3
     1716029.227      382501.414     1715710.087      382207.234
     1715372.197      381949.662
#Sta/Elev= 30
       0 1021.54     9.6 1016.47    19.3 1013.86    57.9 1017.65     164 1016.95
   279.7 1014.61   356.9 1009.85   366.5 1010.89   405.1 1020.78   414.8 1020.14
     434 1014.42   453.9  1005.6     463 1004.97   468.9 1006.15   482.3 1012.58
   501.6 1030.15   520.9 1041.38   530.6 1048.91   578.9 1072.66   588.5 1073.56
   617.5 1070.62   646.5 1059.28   656.1 1057.64   723.7 1054.34     743  1055.7
   762.3  1060.8   791.3 1076.81   810.6 1081.37   839.6 1093.95   858.9 1098.58
#Mann= 3 , 0 , 0
       0      .1       0   453.9    .045       0   468.9      .1       0
#XS Ineff= 2 , 0
          404.78 1020.92
Permanent Ineff=
       F       F
Bank Sta=453.9,468.9
XS Rating Curve= 0 ,0
Exp/Cntr=0.3,0.1