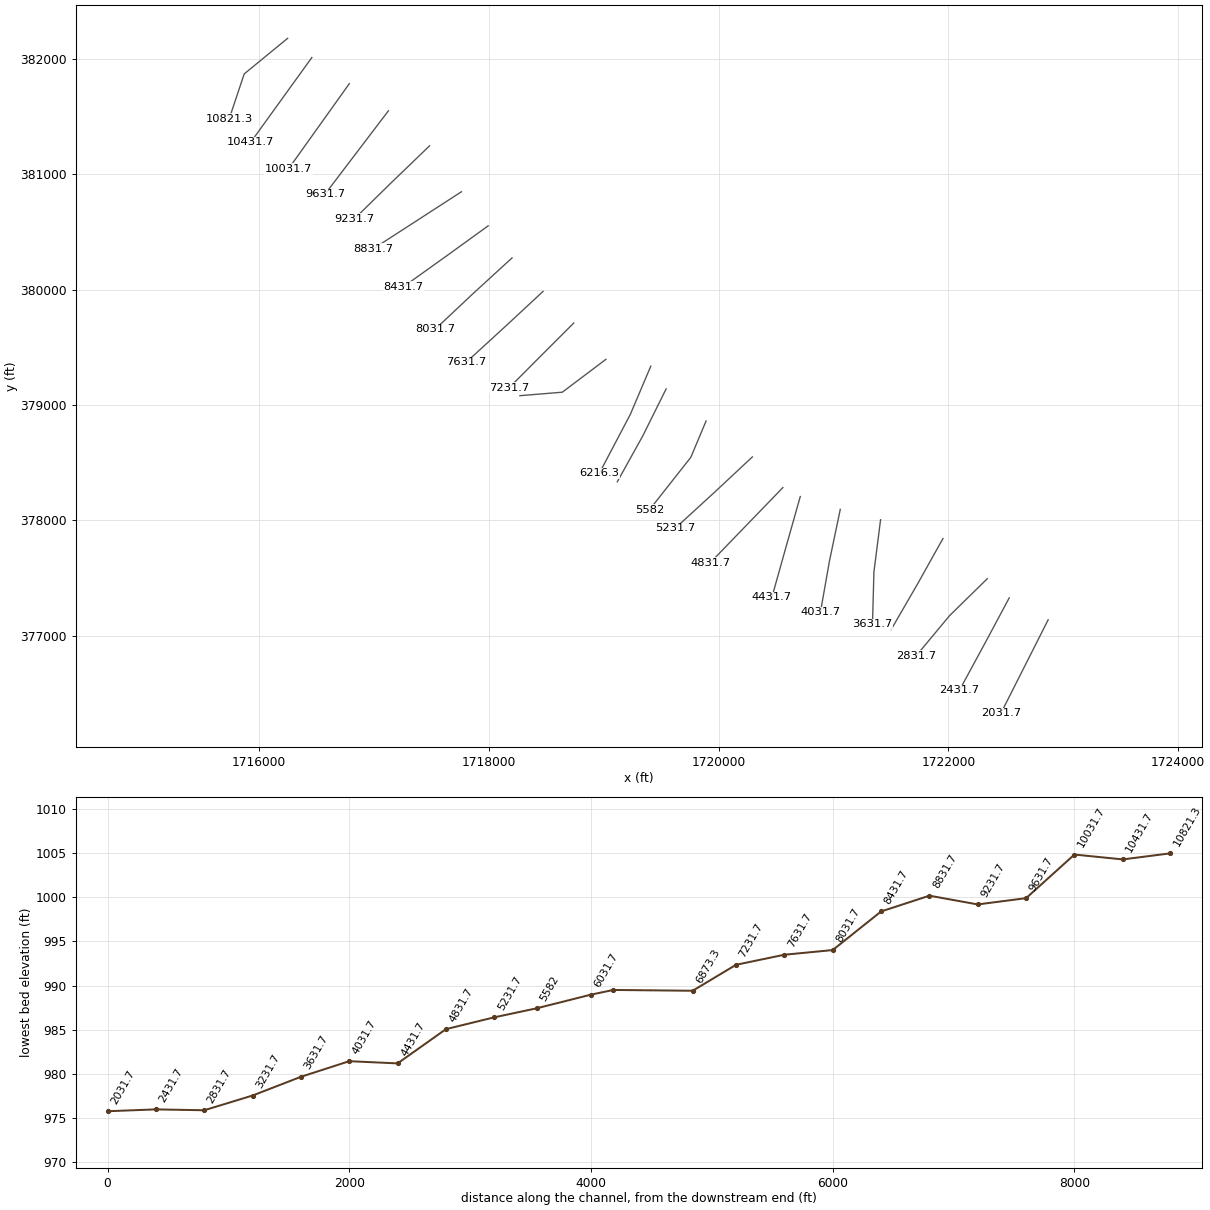
HEC-RAS study DntsRn.prj: DntsRn

--- DntsRn.g01 (geometry) --- (continued)

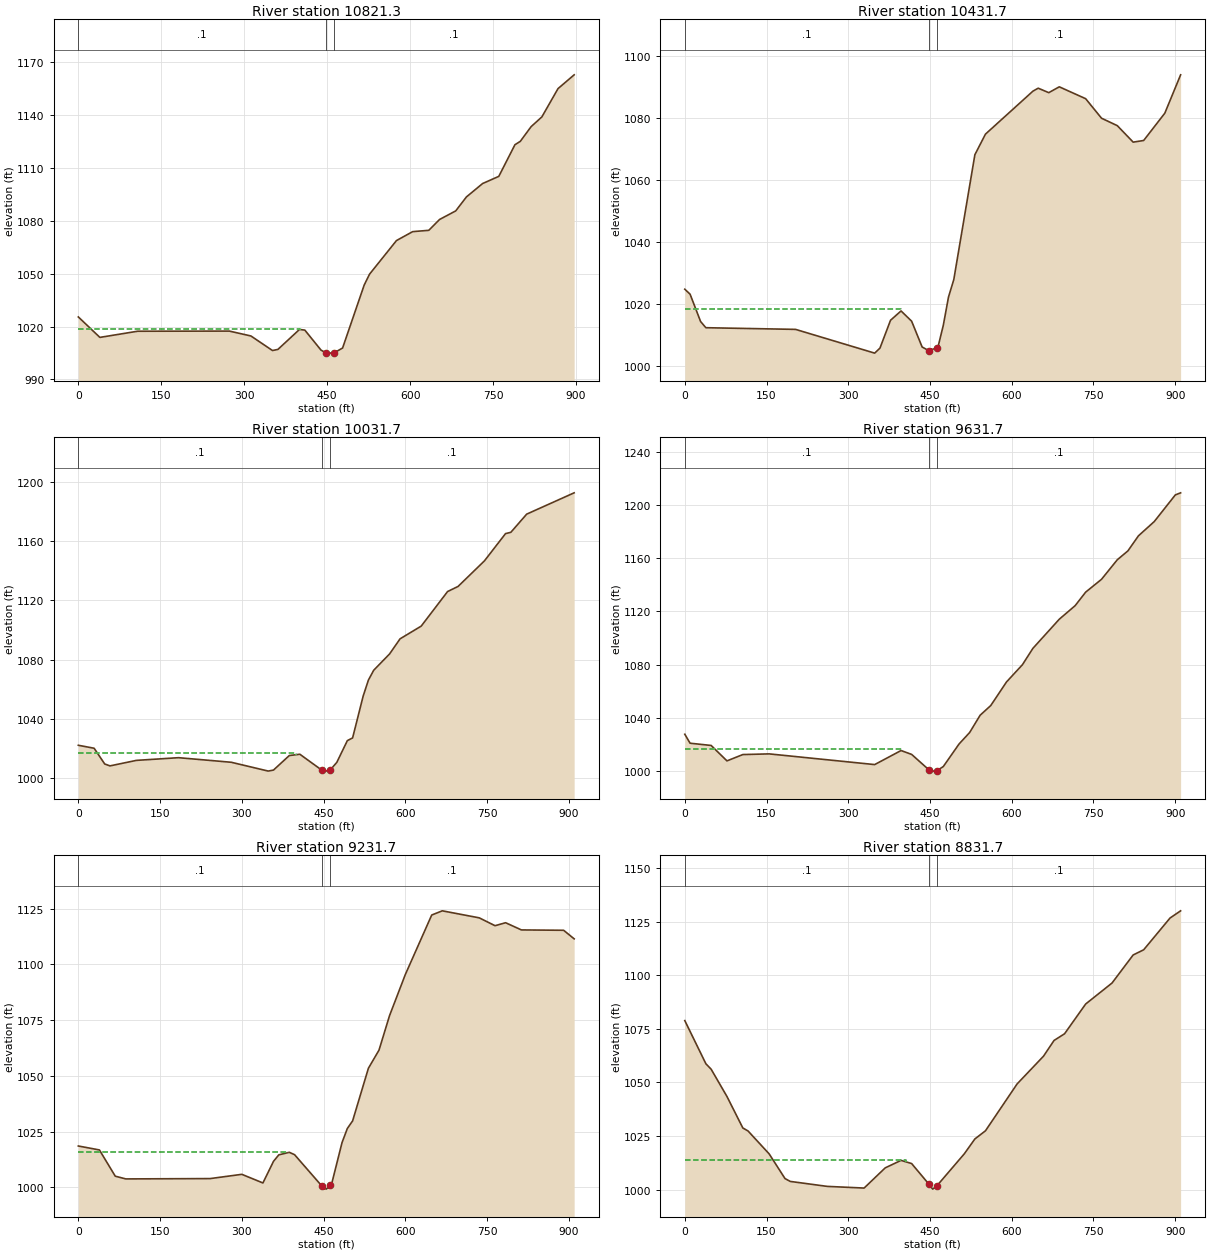
Type RM Length L Ch R = 1 ,10821.3 ,383.711,389.558,395.404
XS GIS Cut Line= 3
     1716248.562      382180.629     1715870.724      381872.113
     1715740.553      381484.371
#Sta/Elev= 30
       0 1025.51      39  1013.9   107.3  1017.4   273.2 1017.48   312.2  1014.7
   351.2 1006.44     361 1007.08     400 1018.41   409.7 1018.03     439 1006.66
   447.5  1005.2   458.5 1004.97   462.5 1005.08     478 1007.89     517 1043.59
   526.7 1049.78   575.4 1068.86   604.7 1073.93   633.9 1074.68   653.3 1080.82
   682.6 1085.71     702 1093.65   731.3 1101.25   760.5 1105.31   789.7 1123.28
   799.4 1125.19   818.9 1133.51   838.4 1139.07   867.6 1155.12   896.8 1162.95
#Mann= 3 , 0 , 0
       0      .1       0   447.5    .045       0   462.5      .1       0
#XS Ineff= 2 , 0
          401.24 1018.71
Permanent Ineff=
       F       F
Bank Sta=447.5,462.5
XS Rating Curve= 0 ,0
Exp/Cntr=0.3,0.1

Type RM Length L Ch R = 1 ,10431.7 ,399.889,400,400.111
XS GIS Cut Line= 3
     1716459.483      382014.345     1716192.674      381645.784
     1715925.864      381277.223
#Sta/Elev= 30
       0 1024.86     9.7 1023.26      29 1014.46    38.7 1012.47   203.3 1011.93
   348.5 1004.29   358.2 1005.91   377.6 1014.87   396.9 1017.87   416.3 1014.57
   435.6 1006.26   447.5 1005.12   462.5 1005.97   464.7 1006.26   474.4 1013.21
     484 1022.35   493.7 1027.96   532.4 1068.14   551.8 1074.76   638.9 1088.59
   648.6 1089.55     668 1088.11   687.3 1089.99   735.7 1086.17   764.8 1079.89
   793.8 1077.49   822.9 1072.19   842.2 1072.72     881 1081.51     910 1093.85
#Mann= 3 , 0 , 0
       0      .1       0   447.5    .045       0   462.5      .1       0
#XS Ineff= 2 , 0
           397.7 1018.42
Permanent Ineff=
       F       F
Bank Sta=447.5,462.5
XS Rating Curve= 0 ,0
Exp/Cntr=0.3,0.1

Type RM Length L Ch R = 1 ,10031.7 ,400.681,400,399.319
XS GIS Cut Line= 3
     1716785.733      381787.705     1716520.762      381417.819
     1716255.791      381047.933
#Sta/Elev= 30
       0 1022.27      29 1020.26    48.4 1009.67    58.1 1008.37   106.5 1012.08
   183.9  1013.9   280.7 1010.81   348.5 1004.88   358.2 1005.56   387.2 1015.35
   406.6 1016.22   447.5 1005.33     455 1004.84   462.5 1005.71   474.4 1010.74
   493.7 1025.38   503.4 1027.25   522.8 1055.48   532.4 1066.23   542.1 1072.84
   571.2 1083.82   590.5 1094.03   629.3  1102.6   677.7 1125.89     697 1129.36
   745.4 1146.61   784.1 1164.97   793.8 1165.83   822.9 1178.09     910 1192.45
#Mann= 3 , 0 , 0
       0      .1       0   447.5    .045       0   462.5      .1       0
#XS Ineff= 2 , 0
          400.35 1017.11
Permanent Ineff=
       F       F
Bank Sta=447.5,462.5
XS Rating Curve= 0 ,0
Exp/Cntr=0.3,0.1

Type RM Length L Ch R = 1 ,9631.7  ,403.472,400,396.73
XS GIS Cut Line= 3
     1717125.502      381551.729     1716849.462       381190.03
     1716573.421      380828.331
#Sta/Elev= 30
       0 1027.62     9.7 1020.89    48.4 1019.19    77.4  1007.6   106.5 1012.35
   154.9 1012.86   348.5 1004.82   396.9 1015.38   416.3 1012.48   447.5 1001.09
     455   999.9   462.5 1000.19   474.4 1003.32   503.4 1020.32   522.8 1028.93
   542.1 1041.95   561.5 1049.18   590.5 1066.97   619.6 1079.87   638.9  1092.2
   687.3  1114.1   716.4 1124.29   735.7 1134.45   764.8  1144.1   793.8 1158.81
   813.2 1165.44   832.6  1176.8   861.6 1187.51   900.3 1207.56     910 1209.12
#Mann= 3 , 0 , 0
       0      .1       0   447.5    .045       0   462.5      .1       0
#XS Ineff= 2 , 0
          398.58 1016.32
Permanent Ineff=
       F       F
Bank Sta=447.5,462.5
XS Rating Curve= 0 ,0
Exp/Cntr=0.3,0.1

Type RM Length L Ch R = 1 ,9231.7  ,404.323,400,395.475
XS GIS Cut Line= 3
     1717484.201      381248.527     1717155.858      380933.547
     1716830.336      380615.616
#Sta/Elev= 30
       0 1018.54    38.7 1016.77    67.8 1004.99    87.1 1003.77     242 1003.92
   300.1 1005.83   338.8 1001.96   358.2 1011.66   367.9 1014.56   387.2 1015.71
   396.9 1014.64   447.5 1000.43     455  999.19   462.5 1000.84   464.7 1001.33
     484 1020.09   493.7 1026.39   503.4 1029.81   532.4 1053.43   551.8 1061.54
   571.2 1077.05   600.2 1095.52   648.6 1122.18     668 1124.06   735.8 1120.91
   764.8 1117.39   784.2 1118.72   813.2 1115.49   890.7 1115.33     910 1111.49
#Mann= 3 , 0 , 0
       0      .1       0   447.5    .045       0   462.5      .1       0
#XS Ineff= 2 , 0
           385.3 1015.79
Permanent Ineff=
       F       F
Bank Sta=447.5,462.5
XS Rating Curve= 0 ,0
Exp/Cntr=0.3,0.1

Type RM Length L Ch R = 1 ,8831.7  ,398.842,400,401.044
XS GIS Cut Line= 3
     1717761.403      380849.947     1717378.995      380603.392
     1716996.587      380356.837
#Sta/Elev= 30
       0 1078.91    38.7 1058.75    48.4 1056.18    77.4 1043.45   106.5 1028.76
   116.2 1027.32   154.9 1016.62   183.9 1005.12   193.6 1003.78   261.4 1001.46
   329.1 1000.68   367.9 1010.12   396.9 1013.61   416.3 1012.13   447.5 1002.66
     455 1000.18   462.5 1001.68   513.1 1016.71   532.4 1023.62   551.8 1027.42
   609.9 1049.32   658.3 1062.27   677.7 1069.63     697 1072.76   735.7 1086.65
   784.1 1096.46   822.9 1109.57   842.2 1111.99   890.6 1126.83     910 1130.19
#Mann= 3 , 0 , 0
       0      .1       0   447.5    .045       0   462.5      .1       0
#XS Ineff= 2 , 0
          406.55 1013.63
Permanent Ineff=
       F       F
Bank Sta=447.5,462.5
XS Rating Curve= 0 ,0
Exp/Cntr=0.3,0.1

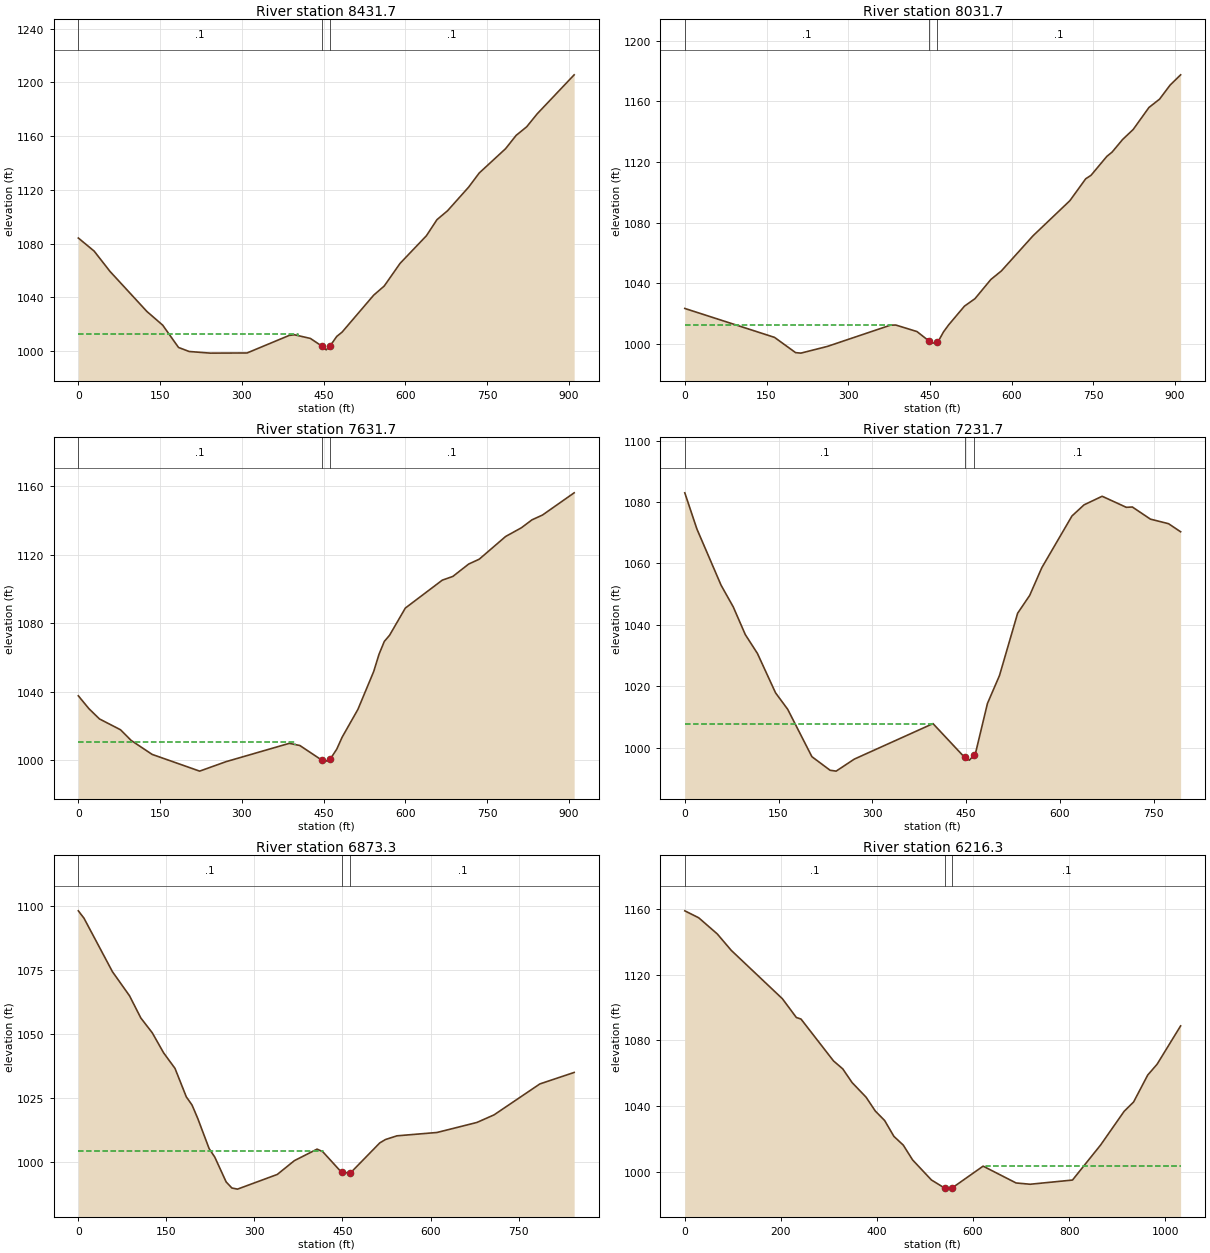
Type RM Length L Ch R = 1 ,8431.7  ,397.397,400,403.008
XS GIS Cut Line= 3
     1717993.845      380554.192     1717624.697      380288.364
     1717254.036      380024.298
#Sta/Elev= 30
       0  1084.1      29 1074.38    58.1 1059.25   125.8 1029.43   154.9 1019.19
   183.9 1002.61   203.3  999.62     242  998.39   309.7  998.51   387.1 1011.59
   396.8 1012.05   425.9 1009.33   447.4 1003.52   454.9 1000.82   462.4 1003.95
   474.3 1010.84     484    1014     542 1041.52   561.4 1048.35   590.5 1065.22
   638.9 1085.82   658.2 1097.77   677.6 1104.39   716.3 1121.97   735.7 1132.49
   784.1  1150.6   803.5 1160.52   822.9 1166.94   842.2 1176.59     910 1205.62
#Mann= 3 , 0 , 0
       0      .1       0   447.4    .045       0   462.4      .1       0
#XS Ineff= 2 , 0
           403.9 1012.76
Permanent Ineff=
       F       F
Bank Sta=447.4,462.4
XS Rating Curve= 0 ,0
Exp/Cntr=0.3,0.1

Type RM Length L Ch R = 1 ,8031.7  ,399.843,400,399.711
XS GIS Cut Line= 3
     1718201.626       380276.12     1717865.327       379969.18
     1717533.329       379658.23
#Sta/Elev= 30
       0 1023.49   164.7 1004.41   203.4  994.35   213.1  994.02   261.6  998.43
   377.8 1012.49   387.5 1012.53   426.2 1008.24   447.8 1002.17   455.3 1000.58
   462.8 1001.35     465 1001.57   474.7  1007.9   484.3 1012.63   513.4 1025.01
   532.7 1029.93   561.8 1042.57   581.1  1048.2   639.2 1071.39   706.9 1094.56
     736 1109.01   745.7 1111.28   774.7 1123.75   784.4  1126.6   803.7 1134.91
   823.1 1141.51   852.1 1156.04   871.5 1161.51   890.8 1170.75   910.2 1177.56
#Mann= 3 , 0 , 0
       0      .1       0   447.8    .045       0   462.8      .1       0
#XS Ineff= 2 , 0
          379.98 1012.83
Permanent Ineff=
       F       F
Bank Sta=447.8,462.8
XS Rating Curve= 0 ,0
Exp/Cntr=0.3,0.1

Type RM Length L Ch R = 1 ,7631.7  ,399.171,400,401.031
XS GIS Cut Line= 3
     1718471.638       379985.69     1718137.694       379676.63
     1717801.622      379369.908
#Sta/Elev= 30
       0 1037.52    19.4 1030.01    38.7 1024.02    77.4 1017.67    96.8 1011.48
   135.5 1003.26   222.7  993.49   271.1  999.02   387.2 1009.73   406.6 1008.46
   447.5  999.79     455  999.36   462.5  1000.6   474.4  1006.4   484.1 1013.29
   513.1 1029.57   542.1 1051.73   551.8 1061.75   561.5 1069.27   571.2 1072.91
   600.2 1088.82     668 1105.13   687.4 1107.31   716.4 1114.53   735.8 1117.38
   784.2 1130.64   813.2 1135.75   832.6 1140.38   851.9 1143.19     910 1156.17
#Mann= 3 , 0 , 0
       0      .1       0   447.5    .045       0   462.5      .1       0
#XS Ineff= 2 , 0
           397.7 1010.32
Permanent Ineff=
       F       F
Bank Sta=447.5,462.5
XS Rating Curve= 0 ,0
Exp/Cntr=0.3,0.1

Type RM Length L Ch R = 1 ,7231.7  ,361.561,358.426,352.756
XS GIS Cut Line= 3
     1718738.904      379711.351     1718416.496      379390.129
     1718177.541      379151.087
#Sta/Elev= 30
       0 1083.02    19.4 1071.22    58.1  1052.9    77.5 1045.86    96.8 1036.83
   116.2 1030.68   145.2 1017.85   164.6 1012.49   203.3  997.06   232.4  992.63
   242.1  992.35   271.1  996.26     397 1007.83   447.6  996.83   455.1  995.91
   462.6  997.53   464.8     998   484.1 1014.39   503.4 1023.52   532.4 1043.79
   551.7 1049.61     571  1058.6   619.3 1075.48   638.6  1079.1   667.6  1081.9
   706.2  1078.3   715.9  1078.4   744.8 1074.45   773.8 1072.96   793.1 1070.33
#Mann= 3 , 0 , 0
       0      .1       0   447.6    .045       0   462.6      .1       0
#XS Ineff= 2 , 0
          397.52 1007.79
Permanent Ineff=
       F       F
Bank Sta=447.6,462.6
XS Rating Curve= 0 ,0
Exp/Cntr=0.3,0.1

Type RM Length L Ch R = 1 ,6873.3  ,647.064,656.997,669.418
XS GIS Cut Line= 3
     1719018.789      379396.589     1718639.324      379111.494
       1718270.5      379081.368
#Sta/Elev= 30
       0 1098.29     9.7 1095.38    58.1 1074.48    87.2 1065.06   106.5 1056.36
   125.9 1050.59   145.3 1042.73   164.7 1036.64     184 1025.49   193.7 1022.32
   203.4  1017.1   222.8 1005.28   232.5 1001.92   251.8  992.24   261.5  989.86
   271.2  989.41     339  995.16   368.1 1000.56   406.8 1005.06   416.5 1004.03
   448.4  995.99   463.4   995.7   513.6  1007.5   523.3 1008.82   542.8 1010.26
     611 1011.57   679.1  1015.5   708.3 1018.47   786.3 1030.57   844.7 1035.06
#Mann= 3 , 0 , 0
       0      .1       0   448.4    .045       0   463.4      .1       0
#XS Ineff= 2 , 0
          417.18 1004.16
Permanent Ineff=
       F       F
Bank Sta=448.4,463.4
XS Rating Curve= 0 ,0
Exp/Cntr=0.3,0.1

Type RM Length L Ch R = 1 ,6216.3  ,184.147,184.577,183.973
XS GIS Cut Line= 3
      1719409.25      379337.006     1719231.079      378918.689
     1718961.419      378408.132
#Sta/Elev= 30
       0 1158.88      29 1154.64    67.7 1144.79    96.7 1134.82   203.2 1105.36
   232.2 1093.97   241.9 1093.01   309.6 1067.51   328.9 1062.66   348.3 1054.33
   377.3 1045.48   396.6 1037.01     416 1031.26   435.3  1021.6   454.7 1016.31
   474.3 1007.24   513.4  995.07   541.1   990.1   552.5   989.5   556.1  990.14
     621 1003.49   689.6  993.25   718.9  992.47     807  995.02   865.7 1016.42
   914.6 1036.89   934.2 1042.53   963.6 1058.92   983.1 1065.51  1032.1 1088.85
#Mann= 3 , 0 , 0
       0      .1       0   541.1    .045       0   556.1      .1       0
#XS Ineff= 2 , 0
                          626.04         1003.68
Permanent Ineff=
       F       F
Bank Sta=541.1,556.1
XS Rating Curve= 0 ,0
Exp/Cntr=0.3,0.1

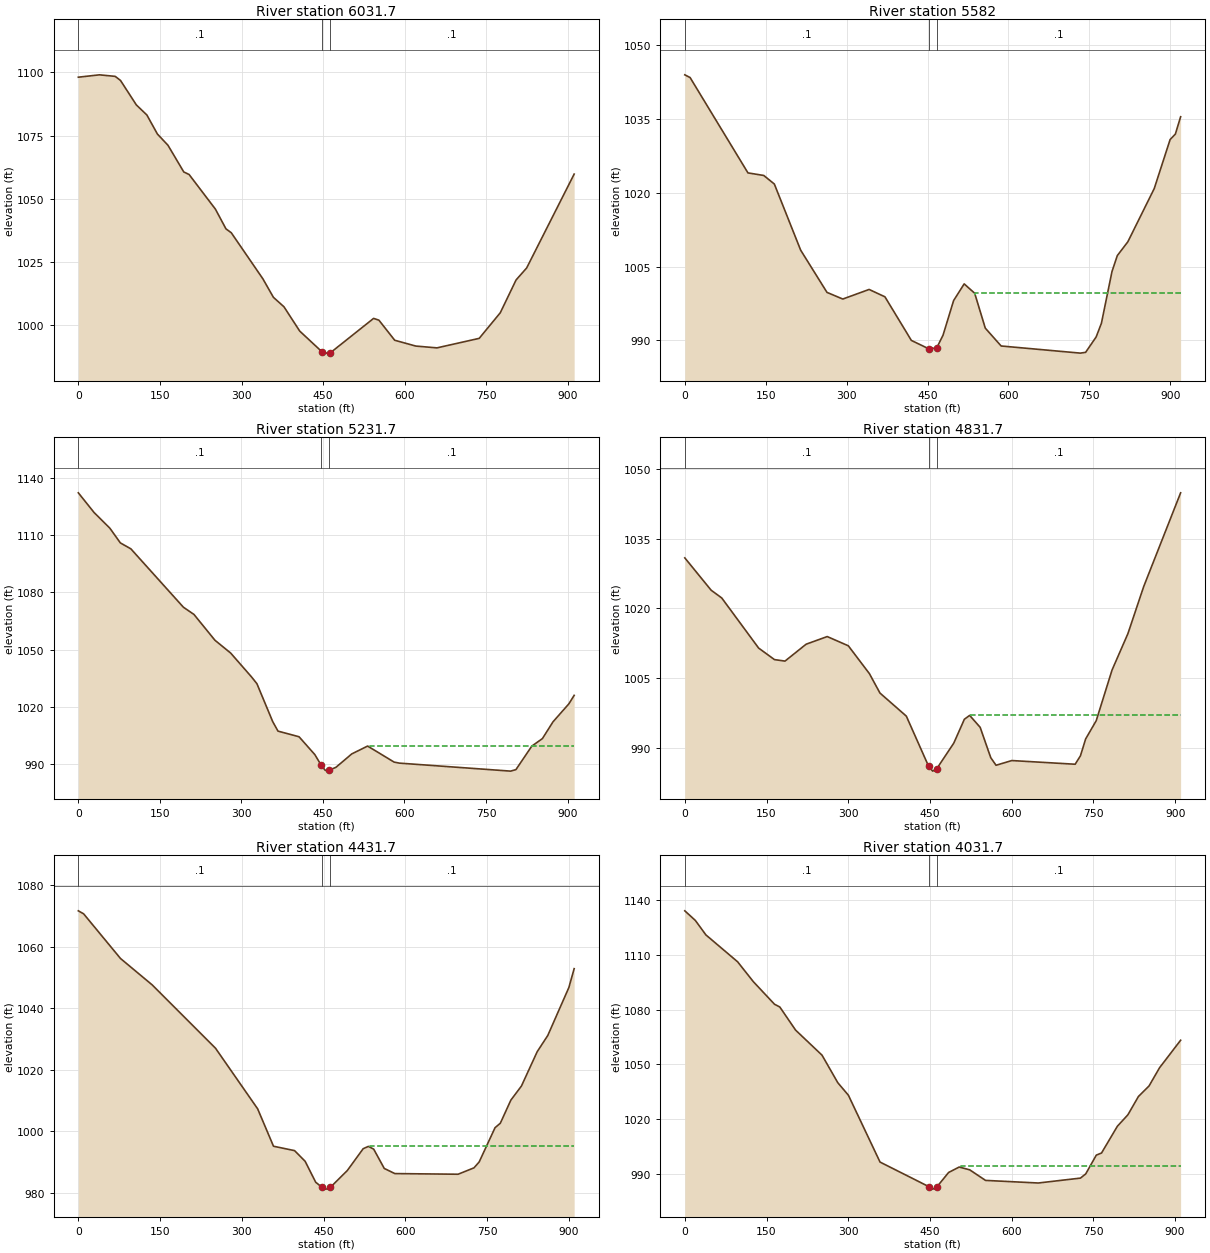
Type RM Length L Ch R = 1 ,6031.7  ,454.521,449.759,446.03
XS GIS Cut Line= 3
     1719542.858      379140.021      1719339.65      378732.494
      1719117.84      378334.429
#Sta/Elev= 30
       0 1098.12    38.8 1099.06    67.8 1098.45    77.5 1096.83   106.6 1087.16
     126 1083.16   145.3 1075.64   164.7  1071.2   193.8 1060.63   203.5 1059.64
   251.9 1045.93   271.3 1038.12     281  1036.6   339.1 1018.37   358.5 1011.04
   377.9 1007.29   406.9  997.67   447.9  989.46   455.4  988.97   462.9  989.07
   542.6 1002.71   552.3 1002.01   581.4  994.06   620.2  991.76     659  991.05
   736.6  994.81   775.3 1004.92   804.4 1017.92   823.8 1022.65   911.1 1059.79
#Mann= 3 , 0 , 0
       0      .1       0   447.9    .045       0   462.9      .1       0
#XS Ineff= 2 , 0
                           552.7         1001.63
Permanent Ineff=
       F       F
Bank Sta=447.9,462.9
XS Rating Curve= 0 ,0
Exp/Cntr=0.3,0.1

Type RM Length L Ch R = 1 ,5582    ,353.588,350.241,346.682
XS GIS Cut Line= 3
      1719890.53       378861.71     1719757.847      378546.852
     1719399.632      378093.914
#Sta/Elev= 30
       0 1043.97     9.8 1043.42   117.1 1024.04   146.4 1023.52     166 1021.78
   214.8 1008.34   263.6  999.76   292.9  998.41   341.7 1000.36     371  998.86
     420     990   451.9  988.32   466.9  988.46   478.7  991.07   498.3   998.1
   517.9 1001.49   537.4  999.58     557   992.5   586.4  988.87   733.2  987.42
     743  987.58   762.5   990.7   772.3   993.5   791.9 1004.01   801.7 1007.23
   821.3 1010.05   870.2 1020.86   899.6 1030.81   909.4 1031.94   919.1 1035.45
#Mann= 3 , 0 , 0
       0      .1       0   451.9    .045       0   466.9      .1       0
#XS Ineff= 2 , 0
                          538.53          999.62
Permanent Ineff=
       F       F
Bank Sta=451.9,466.9
XS Rating Curve= 0 ,0
Exp/Cntr=0.3,0.1

Type RM Length L Ch R = 1 ,5231.7  ,398.849,400,401.364
XS GIS Cut Line= 3
     1720293.481      378550.237     1719960.891       378240.76
     1719622.798      377932.068
#Sta/Elev= 30
       0  1132.2      29 1121.88      58 1113.68    77.3 1105.97    96.7 1102.84
   193.3 1072.27   212.7 1068.49   251.3 1054.97   280.3 1048.24     319 1035.62
   328.6 1032.17   357.6 1012.33   367.3 1007.36     406 1004.41     435  995.08
   446.8  989.49   454.3  986.79   461.8  986.95   473.8  988.38     503  995.42
   532.2  999.53   580.9  991.13   590.7  990.59   795.2   986.4     805   987.2
   834.2   999.5   853.7 1003.44   873.2 1012.23   902.4 1021.66   912.1  1026.1
#Mann= 3 , 0 , 0
       0      .1       0   446.8    .045       0   461.8      .1       0
#XS Ineff= 2 , 0
                          535.87          999.58
Permanent Ineff=
       F       F
Bank Sta=446.8,461.8
XS Rating Curve= 0 ,0
Exp/Cntr=0.3,0.1

Type RM Length L Ch R = 1 ,4831.7  ,388.87,400,411.182
XS GIS Cut Line= 3
     1720558.973      378284.346     1720242.197       377957.73
     1719925.421      377631.114
#Sta/Elev= 30
       0 1030.86    48.4 1023.91    67.8 1022.25   135.5 1011.49   164.6 1009.01
   183.9 1008.69   222.7 1012.32   261.4 1013.96   300.1 1011.98   338.8    1006
   358.2 1001.83   406.6  996.87   447.5   986.1     455  985.06   462.5  985.59
   493.7  991.08   513.1   996.2   522.8  997.03   542.1  994.47   561.5  987.96
   571.2  986.32   600.2  987.33   716.4  986.54   726.1  988.34   735.7  991.98
   755.1  995.89   784.1 1006.76   813.2 1014.57   842.2 1024.69     910 1044.83
#Mann= 3 , 0 , 0
       0      .1       0   447.5    .045       0   462.5      .1       0
#XS Ineff= 2 , 0
                          522.59          997.13
Permanent Ineff=
       F       F
Bank Sta=447.5,462.5
XS Rating Curve= 0 ,0
Exp/Cntr=0.3,0.1

Type RM Length L Ch R = 1 ,4431.7  ,398.44,400,402.23
XS GIS Cut Line= 3
     1720710.375      378206.621     1720586.156      377768.906
     1720462.967      377330.899
#Sta/Elev= 30
       0 1071.62     9.7 1070.65    77.4 1056.13   135.5 1047.56   251.7 1026.99
   329.1 1007.28   358.2  995.12   396.9  993.69   416.3  990.22   435.6  983.43
   447.5  981.73     455  981.18   462.5  981.75   493.7  987.23   522.8  994.32
   532.4  995.07   542.1  994.17   561.5   987.9   580.9  986.23     697  986.02
   726.1  988.09   735.7  990.02   764.8 1001.14   774.5  1002.6   793.8 1010.09
   813.2 1014.67   842.2 1025.85   861.6 1031.11   900.3  1046.7     910 1052.82
#Mann= 3 , 0 , 0
       0      .1       0   447.5    .045       0   462.5      .1       0
#XS Ineff= 2 , 0
                          534.99          995.13
Permanent Ineff=
       F       F
Bank Sta=447.5,462.5
XS Rating Curve= 0 ,0
Exp/Cntr=0.3,0.1

Type RM Length L Ch R = 1 ,4031.7  ,398.201,400,403.33
XS GIS Cut Line= 3
     1721058.547      378095.104      1720964.86      377649.563
      1720885.59      377201.572
#Sta/Elev= 30
       0 1134.22    19.4 1128.94    38.7 1121.01    96.9 1106.26   125.9  1095.3
   164.7 1082.93   174.4 1081.43   203.4 1068.73   251.9 1054.98   280.9 1039.84
   300.3    1033   358.4  996.29   447.8  982.83   455.3  981.43   462.8  982.68
   484.3  990.57   503.7  993.56     523  992.03   552.1  986.22   648.9  984.79
   726.3  987.48     736  989.79   755.4 1000.09     765 1001.26   794.1 1015.95
   813.4 1022.24   832.8 1032.31   852.2 1038.05   871.5 1048.06   910.2 1063.17
#Mann= 3 , 0 , 0
       0      .1       0   447.8    .045       0   462.8      .1       0
#XS Ineff= 2 , 0
                          506.64          993.89
Permanent Ineff=
       F       F
Bank Sta=447.8,462.8
XS Rating Curve= 0 ,0
Exp/Cntr=0.3,0.1

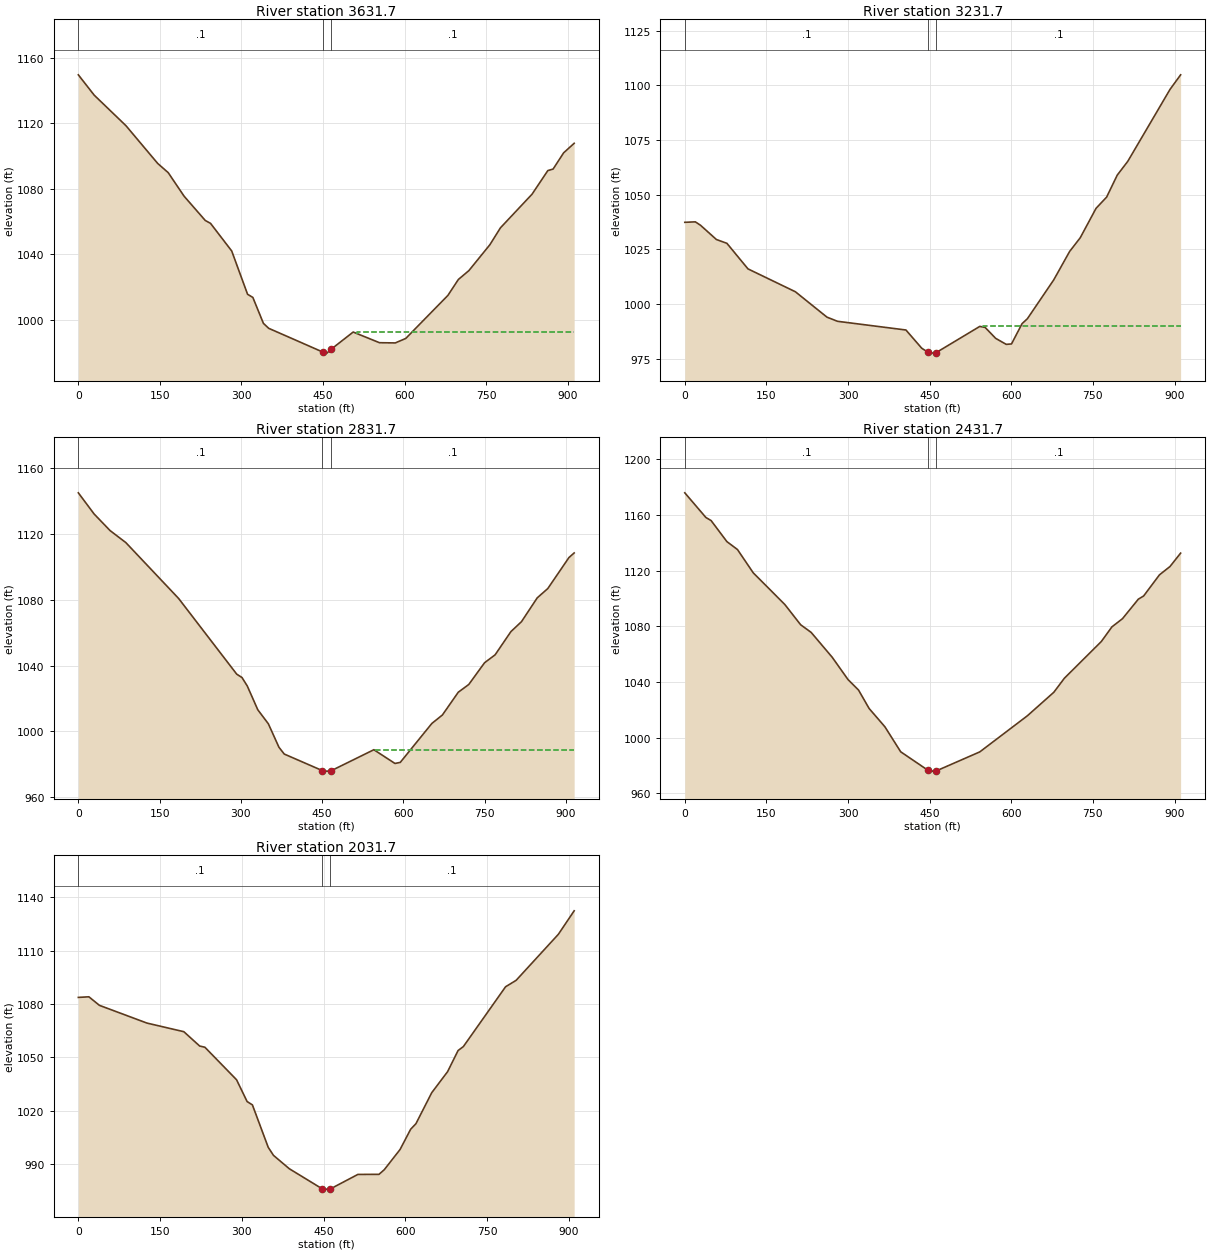
Type RM Length L Ch R = 1 ,3631.7  ,408.661,400,388.739
XS GIS Cut Line= 3
     1721409.247      378005.244     1721351.312      377551.923
     1721338.932      377097.446
#Sta/Elev= 30
       0 1149.65    29.2 1137.23    87.5 1118.61   145.9 1095.54   165.3 1089.89
   194.5 1075.51   233.4 1060.69   243.1 1058.92     282 1042.07   311.2  1015.6
   320.9 1013.68   340.3  997.87     350  994.83   449.5  980.32     457  979.66
   464.5  981.94   505.4  992.54   553.7  986.03   582.8  985.89   602.1  988.64
   679.5  1014.9   698.8 1024.65   718.2 1030.08   756.9 1045.95   776.2 1056.21
   834.3 1076.75   863.3 1091.16     873 1092.09   892.3 1101.98   911.7 1107.82
#Mann= 3 , 0 , 0
       0      .1       0   449.5    .045       0   464.5      .1       0
#XS Ineff= 2 , 0
                          512.84          992.63
Permanent Ineff=
       F       F
Bank Sta=449.5,464.5
XS Rating Curve= 0 ,0
Exp/Cntr=0.3,0.1

Type RM Length L Ch R = 1 ,3231.7  ,406.515,400,396.206
XS GIS Cut Line= 3
     1721952.487       377842.83     1721729.979      377446.241
     1721500.544      377051.647
#Sta/Elev= 30
       0 1037.38    19.4 1037.59      29 1036.01    58.1 1029.51    77.4 1027.77
   116.1 1016.08   203.2 1005.62   261.2  994.01   280.6   992.1   406.4  988.12
   435.4  979.79   447.2  977.91   454.7  977.54   462.2  977.81   542.1  989.76
   551.9  989.31   571.3   984.3   590.7  981.55   600.4  981.74   619.8  991.01
   629.6  993.28   678.1 1011.08   707.2 1024.04   726.7 1030.31   755.8 1043.79
   775.2 1048.91   794.7 1058.96   814.1 1065.28   891.8 1098.22   911.2 1104.85
#Mann= 3 , 0 , 0
       0      .1       0   447.2    .045       0   462.2      .1       0
#XS Ineff= 2 , 0
                          548.27          989.89
Permanent Ineff=
       F       F
Bank Sta=447.2,462.2
XS Rating Curve= 0 ,0
Exp/Cntr=0.3,0.1

Type RM Length L Ch R = 1 ,2831.7  ,393.048,400,404.447
XS GIS Cut Line= 3
     1722338.317      377493.974     1722010.496       377174.28
      1721717.59      376823.317
#Sta/Elev= 30
       0 1145.14    29.2 1132.25    58.5 1122.21    87.7 1114.86   185.1 1080.88
   292.3 1034.85     302 1032.81   311.8 1027.64   331.2 1013.18   350.7 1004.65
   370.2  990.41     380  986.26   450.4  976.17   457.9  975.87   465.4  975.91
   545.4  988.89   584.3  980.54   594.1  981.18   652.4 1004.87   671.9 1010.03
   701.1 1023.84   720.5 1028.56   749.7 1041.81   769.1  1046.6   798.3 1060.73
   817.8 1066.77   846.9 1081.28   866.4 1086.93   905.3 1105.74     915 1108.57
#Mann= 3 , 0 , 0
       0      .1       0   450.4    .045       0   465.4      .1       0
#XS Ineff= 2 , 0
                          547.39          988.95
Permanent Ineff=
       F       F
Bank Sta=450.4,465.4
XS Rating Curve= 0 ,0
Exp/Cntr=0.3,0.1

Type RM Length L Ch R = 1 ,2431.7  ,399.473,400,400.658
XS GIS Cut Line= 3
     1722529.204      377327.913     1722313.994      376927.287
     1722095.734      376526.579
#Sta/Elev= 30
       0 1176.01    38.7  1158.3    48.4 1156.04    77.4 1140.92    96.8 1135.24
   125.8 1118.49   183.8 1095.74   212.9 1081.18   232.2 1075.69   270.9  1057.8
     300 1041.75   319.3 1034.21   338.7    1021   367.7 1007.85   396.7  989.88
   447.3  976.45   454.8  975.97   462.3  976.16   542.1  989.81   629.5 1015.75
   678.1 1032.65   697.5 1042.74   765.4 1069.14   784.9 1079.68   804.3 1085.55
   833.4 1099.58   843.1 1101.85   872.2 1117.05   891.6 1123.05   911.1 1132.67
#Mann= 3 , 0 , 0
       0      .1       0   447.3    .045       0   462.3      .1       0
Bank Sta=447.3,462.3
XS Rating Curve= 0 ,0
Exp/Cntr=0.3,0.1

Type RM Length L Ch R = 1 ,2031.7  ,401.774,400,397.993
XS GIS Cut Line= 3
     1722867.728      377137.399     1722661.891       376731.62
     1722456.054      376325.842
#Sta/Elev= 30
       0 1083.69    19.4 1084.03    38.7 1079.22   125.9 1069.24   193.6 1064.39
   222.7 1056.32   232.3 1055.63   290.4 1037.33   309.8 1025.05   319.5 1023.18
   348.5  999.31   358.2  994.75   387.2  987.24   447.5  975.95     455  975.76
   462.5  975.87   513.1  984.04   551.8  984.08   561.5   986.7   590.5  998.07
   609.9 1009.46   619.6 1012.59   648.6 1030.04   677.7 1041.88     697 1053.79
   706.7 1056.02   784.1 1089.67   803.5  1093.3     881 1119.21     910 1132.43
#Mann= 3 , 0 , 0
       0      .1       0   447.5    .045       0   462.5      .1       0
Bank Sta=447.5,462.5
XS Rating Curve= 0 ,0
Exp/Cntr=0.3,0.1