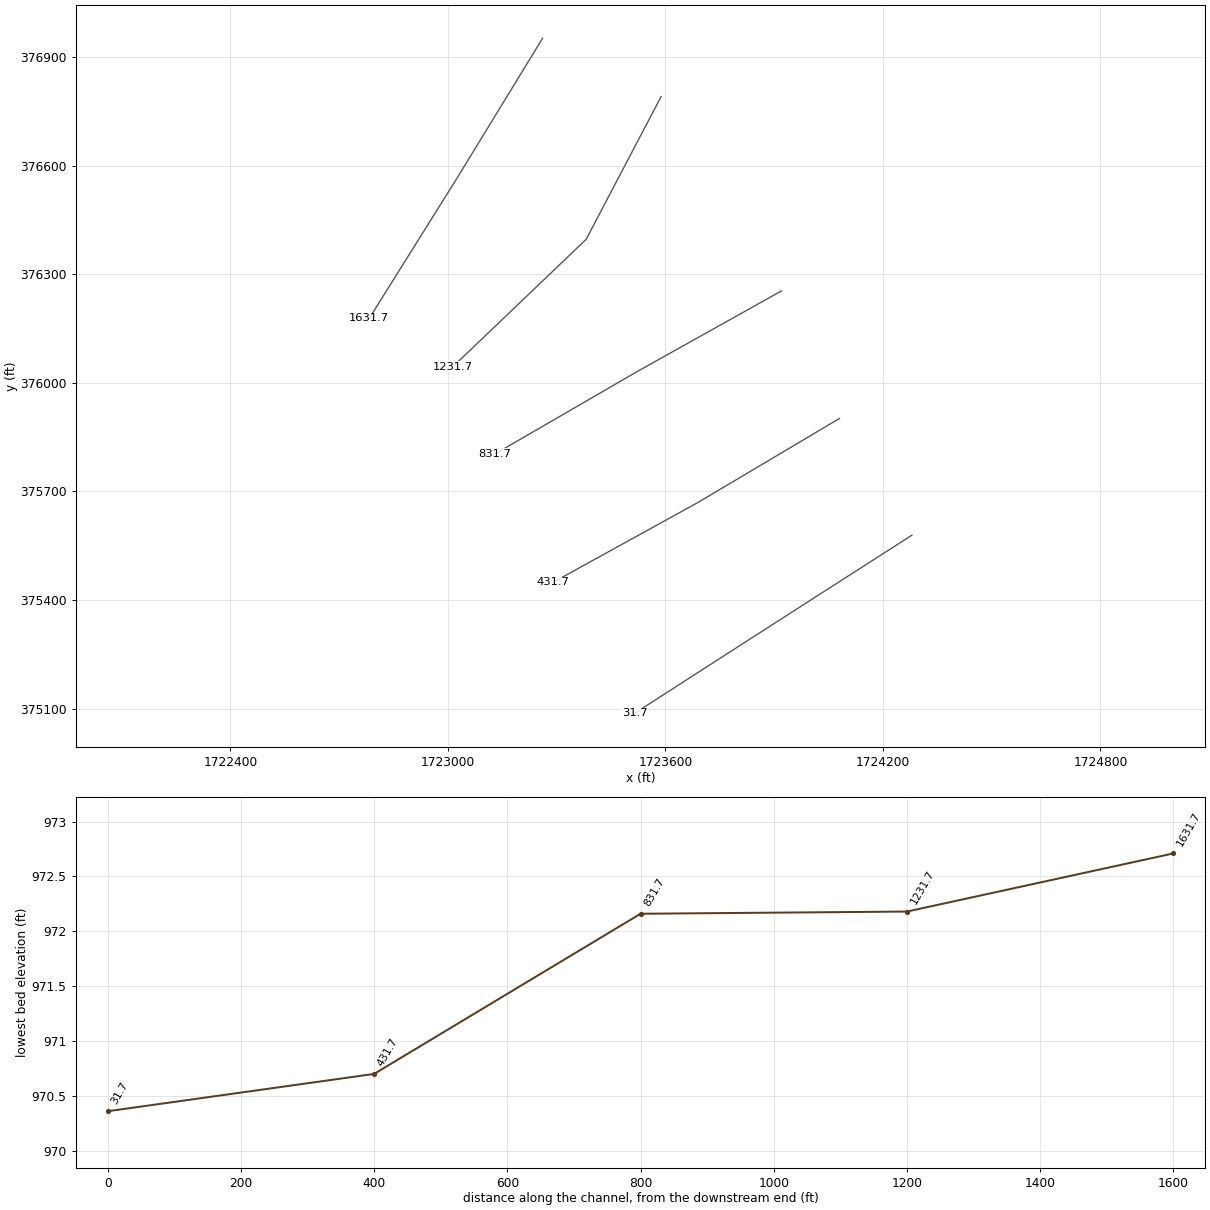
HEC-RAS study DntsRn.prj: DntsRn

--- DntsRn.g01 (geometry) --- (continued)

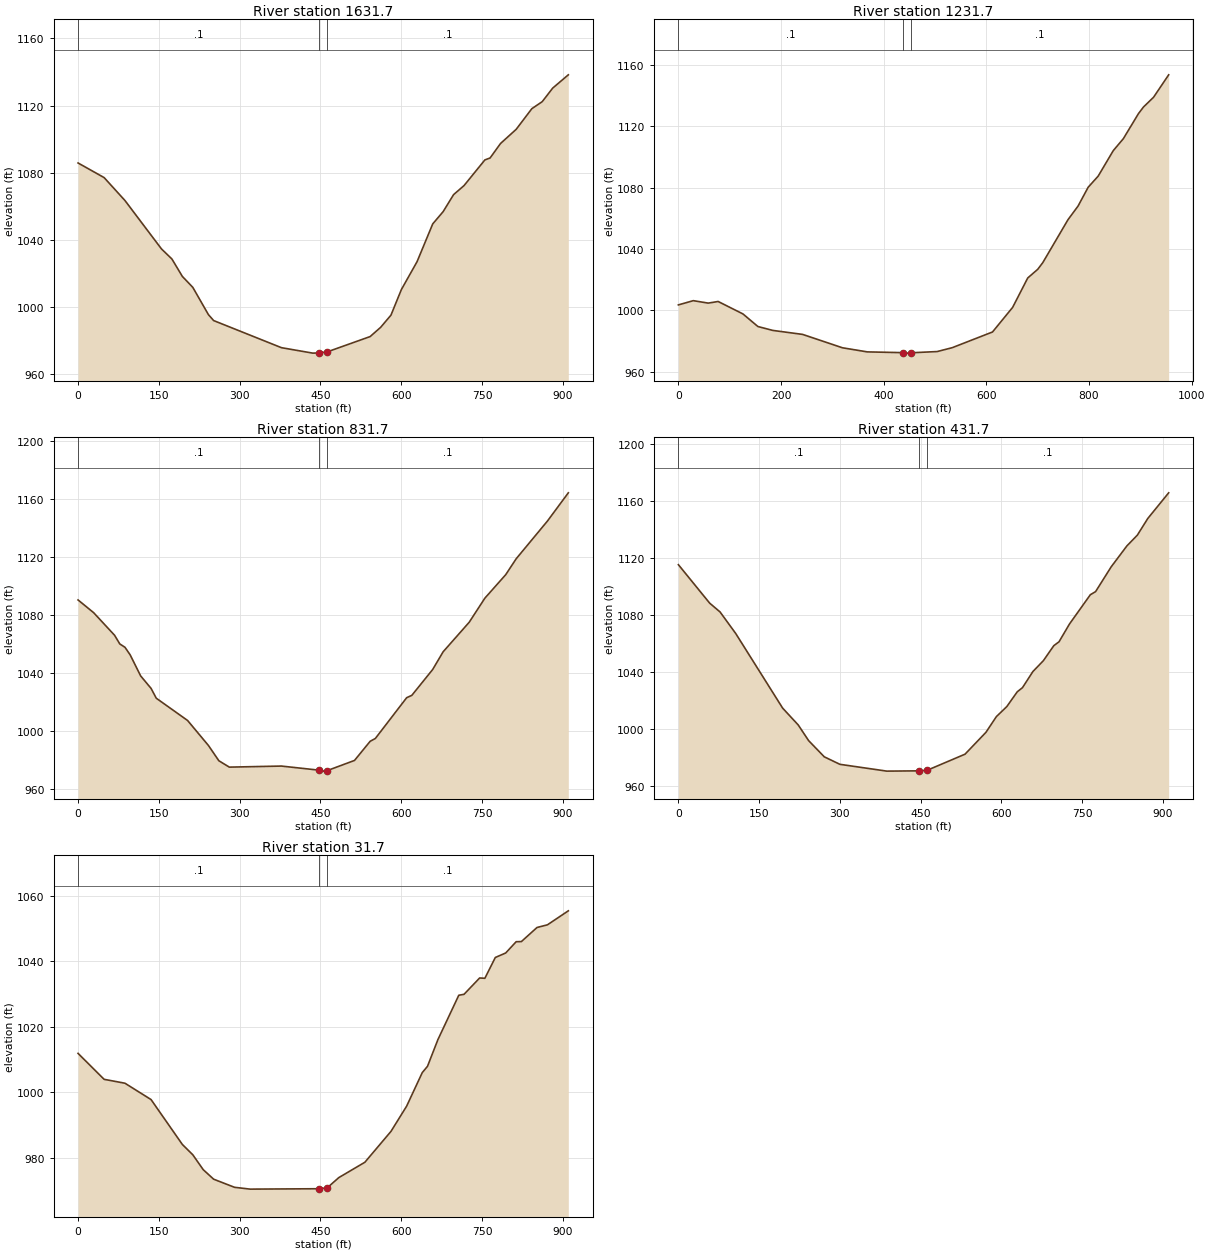
Type RM Length L Ch R = 1 ,1631.7  ,398.537,400,393.365
XS GIS Cut Line= 3
     1723261.144      376952.214     1723024.083       376563.87
     1722782.973      376177.956
#Sta/Elev= 30
       0 1085.82    48.4 1077.12    87.1 1063.47   154.9 1034.67   174.2 1028.71
   193.6 1018.34     213 1011.83     242   995.6   251.7  992.07   377.5  975.95
   435.6  972.71   447.5  972.82   462.5  973.46   542.1  982.55   561.5     988
   580.8   995.3   600.2 1010.56   629.3 1027.14   658.3 1049.56   677.7 1056.89
     697 1066.98   716.4 1072.35   755.1 1087.63   764.8 1088.79   784.2 1097.41
   813.2 1105.82   842.3 1118.11   861.6  1122.3     881 1130.35     910 1138.25
#Mann= 3 , 0 , 0
       0      .1       0   447.5    .045       0   462.5      .1       0
Bank Sta=447.5,462.5
XS Rating Curve= 0 ,0
Exp/Cntr=0.3,0.1

Type RM Length L Ch R = 1 ,1231.7  ,413.079,400,395.607
XS GIS Cut Line= 3
     1723588.138      376791.254     1723381.493      376396.794
     1723013.289      376044.116
#Sta/Elev= 30
       0 1003.63      29 1006.39    58.1  1004.8    77.4 1005.85   125.8  997.73
   154.9  989.53   183.9  986.99     242  984.39   319.5  975.68   367.9  972.99
   437.8  972.49   445.3  972.18   452.8   972.4   504.1   973.2   533.6  975.74
     612  985.97   651.2 1002.01   680.6 1021.18   700.2 1026.87     710 1031.22
   759.1 1059.22   778.7 1068.09   798.3 1080.32   817.9 1087.63   847.3 1104.24
   866.9 1112.02   896.3 1128.34   906.1 1132.66   925.8 1139.05   955.2 1153.66
#Mann= 3 , 0 , 0
       0      .1       0   437.8    .045       0   452.8      .1       0
Bank Sta=437.8,452.8
XS Rating Curve= 0 ,0
Exp/Cntr=0.3,0.1

Type RM Length L Ch R = 1 ,831.7   ,399.403,400,399.517
XS GIS Cut Line= 3
     1723920.067      376254.129     1723523.007      376031.798
     1723129.561      375803.294
#Sta/Elev= 30
       0 1090.32      29 1081.51    67.8 1065.94    77.5 1059.96    87.1 1057.64
    96.8 1052.38   116.2 1037.89   135.6 1029.24   145.2 1022.49   203.3 1007.13
   242.1  989.83   261.4  979.32   280.8  974.92   377.6  975.65   447.6  972.81
   455.1  972.16   462.6  972.53   513.2  979.54   542.2  992.73   551.9   994.7
     610 1022.84   619.6 1024.46   658.4 1042.36   677.7 1054.53   726.1 1074.92
   755.2 1091.55   793.9 1107.76   813.3 1118.73   871.3 1144.76   910.1 1164.26
#Mann= 3 , 0 , 0
       0      .1       0   447.6    .045       0   462.6      .1       0
Bank Sta=447.6,462.6
XS Rating Curve= 0 ,0
Exp/Cntr=0.3,0.1

Type RM Length L Ch R = 1 ,431.7   ,399.219,400,401.543
XS GIS Cut Line= 3
     1724080.197      375901.696     1723689.267      375669.152
     1723290.108      375448.787
#Sta/Elev= 30
       0 1115.29    58.1 1088.36    77.4 1082.19   106.5 1067.09   193.6 1014.86
   222.6 1003.04   241.9  992.08     271  980.72     300  975.47   387.1   970.7
   447.4   970.9   462.4  971.34   532.5  982.57   571.3  997.86   590.7 1008.87
   610.1 1015.91   629.5 1026.26   639.2 1029.16   658.6 1040.46     678 1048.05
   697.4 1058.57   707.1 1061.29   726.5 1073.73   765.3 1094.26     775 1096.41
   804.1 1113.84   833.2 1128.45   852.6 1135.98     872 1147.66   910.8 1165.63
#Mann= 3 , 0 , 0
       0      .1       0   447.4    .045       0   462.4      .1       0
Bank Sta=447.4,462.4
XS Rating Curve= 0 ,0
Exp/Cntr=0.3,0.1

Type RM Length L Ch R = 1 ,31.7    ,32.066,31.744,31.386
XS GIS Cut Line= 3
     1724279.879      375579.047     1723897.064      375333.126
     1723514.648      375086.582
#Sta/Elev= 30
       0 1011.82    48.4 1003.89    87.1  1002.7   135.5  997.71   193.6     984
     213  980.85   232.3  976.31   251.7  973.39   290.4  970.92   319.5  970.36
   447.5  970.48   462.5  970.76     484  973.88   532.4  978.57   580.9  988.01
   609.9   995.7   638.9 1005.94   648.6 1007.86     668 1016.04   706.7 1029.57
   716.4 1029.85   745.4 1034.84   755.1 1034.75   774.5  1041.1   793.8 1042.48
   813.2 1045.92   822.9 1045.96   851.9 1050.26   871.3 1051.08     910 1055.35
#Mann= 3 , 0 , 0
       0      .1       0   447.5    .045       0   462.5      .1       0
Bank Sta=447.5,462.5
XS Rating Curve= 0 ,0
Exp/Cntr=0.3,0.1

Chan Stop Cuts=-1
Use User Specified Reach Order=0